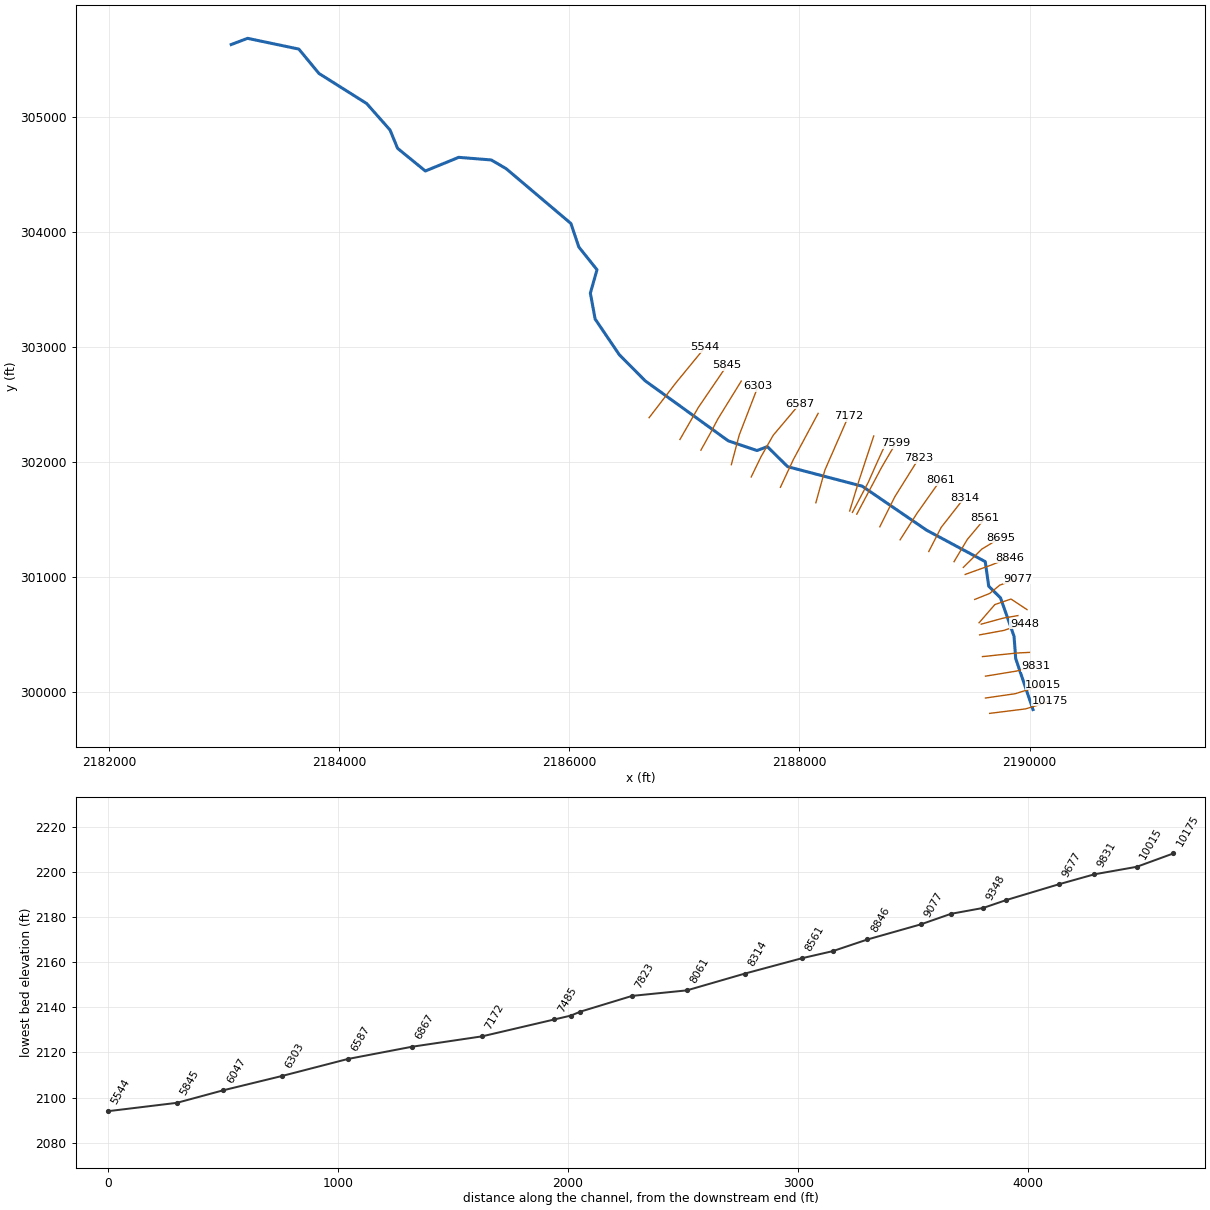
--- SLPHRLCKRN.prj (project) ---

Proj Title=SLPHRLCKRN
Current Plan=p01
Default Exp/Contr=0,0
English Units
Geom File=g01
Flow File=f01
Plan File=p01
BEGIN DESCRIPTION:
Stream Name- Sulphur Lick Run
Flood Zone: Zone A
Greenbrier County, WV
County-Wide Study
WVDHSEM-2018-3, Flood Risk Project
HEC-RAS Version: 5.0.7
General Notes:
For the Hydrology Regression was used.
For the Hydrology Regression with gage weighting was used.
END DESCRIPTION:
DSS Export Rating Curves= 0
DSS Export Rating Curve Sorted= 0
DSS Export Volume Flow Curves= 0
DXF Filename=..\..\..\H1\Remaining\splitted_models\SLPHRLCKRN\GRBRRVTR1.
DXF OffsetX= 0
DXF OffsetY= 0
DXF ScaleX= 0
DXF ScaleY= 0

--- SLPHRLCKRN.p01 (plan) ---

Plan Title=Floodplain
Program Version=5.07
Short Identifier=Floodplain
Geom File=g01
Flow File=f01
Subcritical Flow
K Sum by GR= 0
Std Step Tol= 0.01
Critical Tol= 0.01
Num of Std Step Trials= 20
Max Error Tol= 0.3
Flow Tol Ratio= 0.001
Split Flow NTrial= 30
Split Flow Tol= 0.02
Split Flow Ratio= 0.02
Log Output Level= 0
Friction Slope Method= 1
Unsteady Friction Slope Method= 2
Unsteady Bridges Friction Slope Method= 1
Parabolic Critical Depth
Global Vel Dist= 0 , 0 , 0
Global Log Level= 0
CheckData=True
Encroach Param=-1 ,0,0, 0
Mapping Interval=1HOUR
Computation Time Step Use Courant=        0
Computation Time Step Use Time Series=    0
Computation Time Step Count To Double=0
Computation Time Step Max Doubling=0
Computation Time Step Max Halving=0
Computation Time Step Residence Courant=0
Run HTab= 0
Run UNet= 0
Run Sediment= 0
Run PostProcess= 0
Run WQNet= 0
Run RASMapper= 0
UNET Theta= 0
UNET Theta Warmup= 0
UNET ZTol= 0
UNET ZSATol= 0
UNET MxIter= 0
UNET Max Iter WO Improvement= 0
UNET MaxInSteps= 0
UNET DtIC= 0
UNET DtMin= 0
UNET MaxCRTS= 0
UNET WFStab= 0
UNET SFStab= 0
UNET WFX= 1
UNET SFX= 1
UNET 1D Methodology=Finite Difference
UNET DSS MLevel= 1
UNET Pardiso=0
UNET DZMax Abort= 0
UNET Use Existing IB Tables= 0
UNET Froude Reduction=False
UNET Froude Limit= 0
UNET Froude Power= 0
UNET D1 Cores= 0
UNET D2 Coriolis=0
UNET D2 Cores= 0
UNET D2 Theta= 1
UNET D2 Theta Warmup= 1
UNET D2 Z Tol= 0.01
UNET D2 Volume Tol= 0.01
UNET D2 Max Iterations= 20
UNET D2 Equation= 0
UNET D2 RampUpFraction=0.1
UNET D2 TimeSlices= 1
UNET D2 BCVolumeCheck=0
UNET D1D2 MaxIter= 0
UNET D1D2 ZTol=0.01
UNET D1D2 QTol=0.1
UNET D1D2 MinQTol=1
Write IC File= 0
Write IC File at Fixed DateTime=0
Write IC File at Sim End=0
Echo Input=False
Echo Parameters=False
Echo Output=False
Write Detailed= 0
HDF Write Warmup=0
HDF Write Time Slices=0
HDF Flush=0
HDF Face Node Velocities=0
HDF Compression= 1
HDF Chunk Size= 1
HDF Spatial Parts= 1
HDF Use Max Rows=0
HDF Fixed Rows= 1
Calibration Method= 0
Calibration Iterations= 20
Calibration Max Change=0.05
Calibration Tolerance=0.2
Calibration Maximum=1.5
Calibration Minimum=0.5
Calibration Optimization Method= 1
WQ AD Non Conservative
WQ ULTIMATE=-1
WQ Max Comp Step=1HOUR
WQ Output Interval=15MIN
WQ Output Selected Increments= 0
WQ Output face flow=0
WQ Output face velocity=0
WQ Output face area=0
WQ Output face dispersion=0
WQ Output cell volume=0
WQ Output cell surface area=0
WQ Output cell continuity=0
WQ Output cumulative cell continuity=0
WQ Output face conc=0
WQ Output face dconc_dx=0
WQ Output face courant=0
WQ Output face peclet=0
WQ Output face adv mass=0
WQ Output face disp mass=0
WQ Output cell mass=0
WQ Output cell source sink temp=0
WQ Output nsm pathways=0
WQ Output nsm derived pathways=0
WQ Output MaxMinRange=-1
WQ Daily Max Min Mean=-1
WQ Daily Range=0
WQ Daily Time=0
WQ Create Restart=0
WQ Fixed Restart=0
WQ System Summary=0
WQ Write To DSS=0
WQ Use Fixed Temperature=0
Sorting and Armoring Iterations= 10
XS Update Threshold= 0.02
Bed Roughness Predictor= 0
Hydraulics Update Threshold= 0.02
Energy Slope Method= 1
Volume Change Method= 1
Sediment Retention Method= 0
XS Weighting Method= 0
Number of US Weighted Cross Sections= 1
Number of DS Weighted Cross Sections= 1
Upstream XS Weight=0
Main XS Weight=1
Downstream XS Weight=0
Number of DS XS's Weighted with US Boundary= 1
Upstream Boundary Weight= 1
Weight of XSs Associated with US Boundary= 0
Number of US XS's Weighted with DS Boundary= 1
Downstream Boundary Weight= 0.5
Weight of XSs Associated with DS Boundary= 0.5
Percentile Method= 0
Sediment Output Level= 3
Mass or Volume Output= 0
Output Increment Type= 1
Profile and TS Output Increment= 1
XS Output Flag= 0
XS Output Increment= 10
Write Gradation File= 0
Read Gradation Hotstart= 0
Write HDF5 File= 1
Write Binary Output= 1
Write DSS Sediment File= 0
SV Curve= 0
Specific Gage Flag= 0

--- SLPHRLCKRN.f01 (steady flow) ---

Flow Title=Flow
Program Version=5.07
Number of Profiles= 6
Profile Names=f1p,f10p,f4p,f2p,f02p,f1pplus
River Rch & RM=ANGLINSCK,Main            ,2340
     793     424     561     673    1100    1170
River Rch & RM=GRBRRVTR1,Main            ,3569
    2910    1640    2110    2500    3940    4300
River Rch & RM=GRBRRVTR2,Main            ,9545
     560     296     393     474     782     828
River Rch & RM=GRBRRVTR2,Main            ,7917
     649     344     457     550     904     959
River Rch & RM=GRBRRVTR2,Main            ,7251
     724     386     511     614    1010    1070
River Rch & RM=GRBRRVTR2,Main            ,4027
     806     432     570     684    1120    1190
River Rch & RM=GRBRRVTR2,Main            ,1559
     930     501     660     790    1290    1370
River Rch & RM=GRBRRVTR4,Main            ,4216
     543     287     381     460     760     804
River Rch & RM=GRBRRVTR4,Main            ,3623
     606     321     426     513     846     896
River Rch & RM=HOMINYCK,Main            ,7588
     529     279     371     448     740     622
River Rch & RM=HOMINYCK,Main            ,7193
     857     460     607     728    1190    1009
River Rch & RM=HOMINYCK,Main            ,4145
     967     521     687     822    1340    1138
River Rch & RM=HOMINYCK,Main            ,2465
    1170     637     836     998    1620    1377
River Rch & RM=HOWARDCK,Main            ,24471
    4190    2090    2840    3490    6010    4930
River Rch & RM=HOWARDCK,Main            ,16737
    4520    2250    3060    3770    6510    5330
River Rch & RM=HOWARDCK,Main            ,13262
    4810    2390    3250    4000    6930    5670
River Rch & RM=HOWARDCK,Main            ,1989
    7950    3720    5200    6510   11800    9500
River Rch & RM=JERCHODFT,Main            ,17171
    1090     470     685     878    1670    1320
River Rch & RM=JERCHODFT,Main            ,7552
    1770     752    1110    1420    2730    2160
River Rch & RM=JERCHODFT,Main            ,5826
    1950     834    1220    1570    3000    2370
River Rch & RM=JERCHODFT,Main            ,3691
    2760    1160    1710    2210    4260    3360
River Rch & RM=JERCHODFT,Main            ,644
    3040    1290    1890    2440    4690    3710
River Rch & RM=JERCHODFTT1,Main            ,11960
     564     219     337     445     900     699
River Rch & RM=JERCHODFTT1,Main            ,7657
     832     343     511     664    1290    1020
River Rch & RM=LITTLECK2,Main            ,2947
     715     381     505     607     995    1060
River Rch & RM=LITTLECK2,Main            ,2406
     819     439     580     696    1140    1210
River Rch & RM=SLPHRLCKRN,Main            ,10175
    1700     901    1190    1440    2390    1980
River Rch & RM=SLPHRLCKRN,Main            ,6047
    1890    1000    1320    1600    2640    2200
River Rch & RM=SLSHLCKRN,Main            ,7923
    1880     904    1250    1560    2750    2240
River Rch & RM=YOUNGSCK,Main            ,16001
     751     401     531     637    1040    1110
River Rch & RM=YOUNGSCK,Main            ,13947
     843     452     597     716    1170    1250
River Rch & RM=YOUNGSCK,Main            ,9951
     939     506     667     799    1300    1390
River Rch & RM=YOUNGSCK,Main            ,4914
    1050     567     746     893    1450    1550
Boundary for River Rch & Prof#=ANGLINSCK,Main            , 1
Up Type= 0
Dn Type= 3
Dn Slope=0.00963
Boundary for River Rch & Prof#=ANGLINSCK,Main            , 2
Up Type= 0
Dn Type= 3
Dn Slope=0.00963
Boundary for River Rch & Prof#=ANGLINSCK,Main            , 3
Up Type= 0
Dn Type= 3
Dn Slope=0.00963
Boundary for River Rch & Prof#=ANGLINSCK,Main            , 4
Up Type= 0
Dn Type= 3
Dn Slope=0.00963
Boundary for River Rch & Prof#=ANGLINSCK,Main            , 5
Up Type= 0
Dn Type= 3
Dn Slope=0.00963
Boundary for River Rch & Prof#=ANGLINSCK,Main            , 6
Up Type= 0
Dn Type= 3
Dn Slope=0.00963
Boundary for River Rch & Prof#=GRBRRVTR1,Main            , 1
Up Type= 0
Dn Type= 3
Dn Slope=0.01784
Boundary for River Rch & Prof#=GRBRRVTR1,Main            , 2
Up Type= 0
Dn Type= 3
Dn Slope=0.01784
Boundary for River Rch & Prof#=GRBRRVTR1,Main            , 3
Up Type= 0
Dn Type= 3
Dn Slope=0.01784
Boundary for River Rch & Prof#=GRBRRVTR1,Main            , 4
Up Type= 0
Dn Type= 3
Dn Slope=0.01784
Boundary for River Rch & Prof#=GRBRRVTR1,Main            , 5
Up Type= 0
Dn Type= 3
Dn Slope=0.01784
Boundary for River Rch & Prof#=GRBRRVTR1,Main            , 6
Up Type= 0
Dn Type= 3
Dn Slope=0.01784
Boundary for River Rch & Prof#=GRBRRVTR2,Main            , 1
Up Type= 0
Dn Type= 3
Dn Slope=0.01456
Boundary for River Rch & Prof#=GRBRRVTR2,Main            , 2
Up Type= 0
Dn Type= 3
Dn Slope=0.01456
Boundary for River Rch & Prof#=GRBRRVTR2,Main            , 3
Up Type= 0
Dn Type= 3
Dn Slope=0.01456
Boundary for River Rch & Prof#=GRBRRVTR2,Main            , 4
Up Type= 0
Dn Type= 3
Dn Slope=0.01456
Boundary for River Rch & Prof#=GRBRRVTR2,Main            , 5
Up Type= 0
Dn Type= 3
Dn Slope=0.01456
Boundary for River Rch & Prof#=GRBRRVTR2,Main            , 6
Up Type= 0
Dn Type= 3
Dn Slope=0.01456
Boundary for River Rch & Prof#=GRBRRVTR4,Main            , 1
Up Type= 0
Dn Type= 3
Dn Slope=0.00727
Boundary for River Rch & Prof#=GRBRRVTR4,Main            , 2
Up Type= 0
Dn Type= 3
Dn Slope=0.00727
Boundary for River Rch & Prof#=GRBRRVTR4,Main            , 3
Up Type= 0
Dn Type= 3
Dn Slope=0.00727
Boundary for River Rch & Prof#=GRBRRVTR4,Main            , 4
Up Type= 0
Dn Type= 3
Dn Slope=0.00727
Boundary for River Rch & Prof#=GRBRRVTR4,Main            , 5
Up Type= 0
Dn Type= 3
Dn Slope=0.00727
Boundary for River Rch & Prof#=GRBRRVTR4,Main            , 6
Up Type= 0
Dn Type= 3
Dn Slope=0.00727
Boundary for River Rch & Prof#=HOMINYCK,Main            , 1
Up Type= 0
Dn Type= 3
Dn Slope=0.02963
Boundary for River Rch & Prof#=HOMINYCK,Main            , 2
Up Type= 0
Dn Type= 3
Dn Slope=0.02963
Boundary for River Rch & Prof#=HOMINYCK,Main            , 3
Up Type= 0
Dn Type= 3
Dn Slope=0.02963
Boundary for River Rch & Prof#=HOMINYCK,Main            , 4
Up Type= 0
Dn Type= 3
Dn Slope=0.02963
Boundary for River Rch & Prof#=HOMINYCK,Main            , 5
Up Type= 0
Dn Type= 3
Dn Slope=0.02963
Boundary for River Rch & Prof#=HOMINYCK,Main            , 6
Up Type= 0
Dn Type= 3
Dn Slope=0.02963
Boundary for River Rch & Prof#=HOWARDCK,Main            , 1
Up Type= 0
Dn Type= 1
Dn Known WS=1885.77
Boundary for River Rch & Prof#=HOWARDCK,Main            , 2
Up Type= 0
Dn Type= 1
Dn Known WS=1884.59
Boundary for River Rch & Prof#=HOWARDCK,Main            , 3
Up Type= 0
Dn Type= 1
Dn Known WS=1885.21
Boundary for River Rch & Prof#=HOWARDCK,Main            , 4
Up Type= 0
Dn Type= 1
Dn Known WS=1885.53
Boundary for River Rch & Prof#=HOWARDCK,Main            , 5
Up Type= 0
Dn Type= 1
Dn Known WS=1886.34
Boundary for River Rch & Prof#=HOWARDCK,Main            , 6
Up Type= 0
Dn Type= 1
Dn Known WS=1886.04
Boundary for River Rch & Prof#=JERCHODFT,Main            , 1
Up Type= 0
Dn Type= 3
Dn Slope=0.00689
Boundary for River Rch & Prof#=JERCHODFT,Main            , 2
Up Type= 0
Dn Type= 3
Dn Slope=0.00689
Boundary for River Rch & Prof#=JERCHODFT,Main            , 3
Up Type= 0
Dn Type= 3
Dn Slope=0.00689
Boundary for River Rch & Prof#=JERCHODFT,Main            , 4
Up Type= 0
Dn Type= 3
Dn Slope=0.00689
Boundary for River Rch & Prof#=JERCHODFT,Main            , 5
Up Type= 0
Dn Type= 3
Dn Slope=0.00689
Boundary for River Rch & Prof#=JERCHODFT,Main            , 6
Up Type= 0
Dn Type= 3
Dn Slope=0.00689
Boundary for River Rch & Prof#=JERCHODFTT1,Main            , 1
Up Type= 0
Dn Type= 3
Dn Slope=0.01752
Boundary for River Rch & Prof#=JERCHODFTT1,Main            , 2
Up Type= 0
Dn Type= 3
Dn Slope=0.01752
Boundary for River Rch & Prof#=JERCHODFTT1,Main            , 3
Up Type= 0
Dn Type= 3
Dn Slope=0.01752
Boundary for River Rch & Prof#=JERCHODFTT1,Main            , 4
Up Type= 0
Dn Type= 3
Dn Slope=0.01752
Boundary for River Rch & Prof#=JERCHODFTT1,Main            , 5
Up Type= 0
Dn Type= 3
Dn Slope=0.01752
Boundary for River Rch & Prof#=JERCHODFTT1,Main            , 6
Up Type= 0
Dn Type= 3
Dn Slope=0.01752
Boundary for River Rch & Prof#=LITTLECK2,Main            , 1
Up Type= 0
Dn Type= 3
Dn Slope=0.00092
Boundary for River Rch & Prof#=LITTLECK2,Main            , 2
Up Type= 0
Dn Type= 3
Dn Slope=0.00092
Boundary for River Rch & Prof#=LITTLECK2,Main            , 3
Up Type= 0
Dn Type= 3
Dn Slope=0.00092
Boundary for River Rch & Prof#=LITTLECK2,Main            , 4
Up Type= 0
Dn Type= 3
Dn Slope=0.00092
Boundary for River Rch & Prof#=LITTLECK2,Main            , 5
Up Type= 0
Dn Type= 3
Dn Slope=0.00092
Boundary for River Rch & Prof#=LITTLECK2,Main            , 6
Up Type= 0
Dn Type= 3
Dn Slope=0.00092
Boundary for River Rch & Prof#=SLPHRLCKRN,Main            , 1
Up Type= 0
Dn Type= 3
Dn Slope=0.01995
Boundary for River Rch & Prof#=SLPHRLCKRN,Main            , 2
Up Type= 0
Dn Type= 3
Dn Slope=0.01995
Boundary for River Rch & Prof#=SLPHRLCKRN,Main            , 3
Up Type= 0
Dn Type= 3
Dn Slope=0.01995
Boundary for River Rch & Prof#=SLPHRLCKRN,Main            , 4
Up Type= 0
Dn Type= 3
Dn Slope=0.01995
Boundary for River Rch & Prof#=SLPHRLCKRN,Main            , 5
Up Type= 0
Dn Type= 3
Dn Slope=0.01995
Boundary for River Rch & Prof#=SLPHRLCKRN,Main            , 6
Up Type= 0
Dn Type= 3
Dn Slope=0.01995
Boundary for River Rch & Prof#=SLSHLCKRN,Main            , 1
Up Type= 0
Dn Type= 3
Dn Slope=0.01085
Boundary for River Rch & Prof#=SLSHLCKRN,Main            , 2
Up Type= 0
Dn Type= 3
Dn Slope=0.01085
Boundary for River Rch & Prof#=SLSHLCKRN,Main            , 3
Up Type= 0
Dn Type= 3
Dn Slope=0.01085
Boundary for River Rch & Prof#=SLSHLCKRN,Main            , 4
Up Type= 0
Dn Type= 3
Dn Slope=0.01085
Boundary for River Rch & Prof#=SLSHLCKRN,Main            , 5
Up Type= 0
Dn Type= 3
Dn Slope=0.01085
Boundary for River Rch & Prof#=SLSHLCKRN,Main            , 6
Up Type= 0
Dn Type= 3
Dn Slope=0.01085
Boundary for River Rch & Prof#=YOUNGSCK,Main            , 1
Up Type= 0
Dn Type= 3
Dn Slope=0.02815
Boundary for River Rch & Prof#=YOUNGSCK,Main            , 2
Up Type= 0
Dn Type= 3
Dn Slope=0.02815
Boundary for River Rch & Prof#=YOUNGSCK,Main            , 3
Up Type= 0
Dn Type= 3
Dn Slope=0.02815
Boundary for River Rch & Prof#=YOUNGSCK,Main            , 4
Up Type= 0
Dn Type= 3
Dn Slope=0.02815
Boundary for River Rch & Prof#=YOUNGSCK,Main            , 5
Up Type= 0
Dn Type= 3
Dn Slope=0.02815
Boundary for River Rch & Prof#=YOUNGSCK,Main            , 6
Up Type= 0
Dn Type= 3
Dn Slope=0.02815
DSS Import GetInterval= 0
DSS Import GetPeak= 0
DSS Import FillOption= 0

--- SLPHRLCKRN.g01 (geometry) ---

Geom Title=Geometry
Program Version=5.07

River Reach=SLPHRLCKRN      ,Main
Reach XY= 30
     2190028.687      299850.672     2189878.352      300294.258
     2189864.037      300487.947     2189746.772      300821.122
     2189643.918      300923.422     2189613.902      301136.818
     2189105.108      301409.753      2188545.45      301792.298
     2187897.114      301962.377     2187720.824      302136.617
     2187631.125      302102.558     2187381.175      302186.976
     2186660.416      302708.042     2186434.479       302935.82
     2186224.545      303246.185     2186183.102      303471.409
     2186240.819      303674.442     2186082.821      303872.459
     2186014.159      304076.677     2185450.261      304554.254
     2185321.805      304629.146     2185039.399      304651.864
     2184749.521      304533.113     2184508.446       304730.01
     2184442.432      304889.768     2184239.654      305119.755
     2183825.061      305381.287     2183650.323      305593.026
     2183204.837      305686.521     2183062.817      305632.638

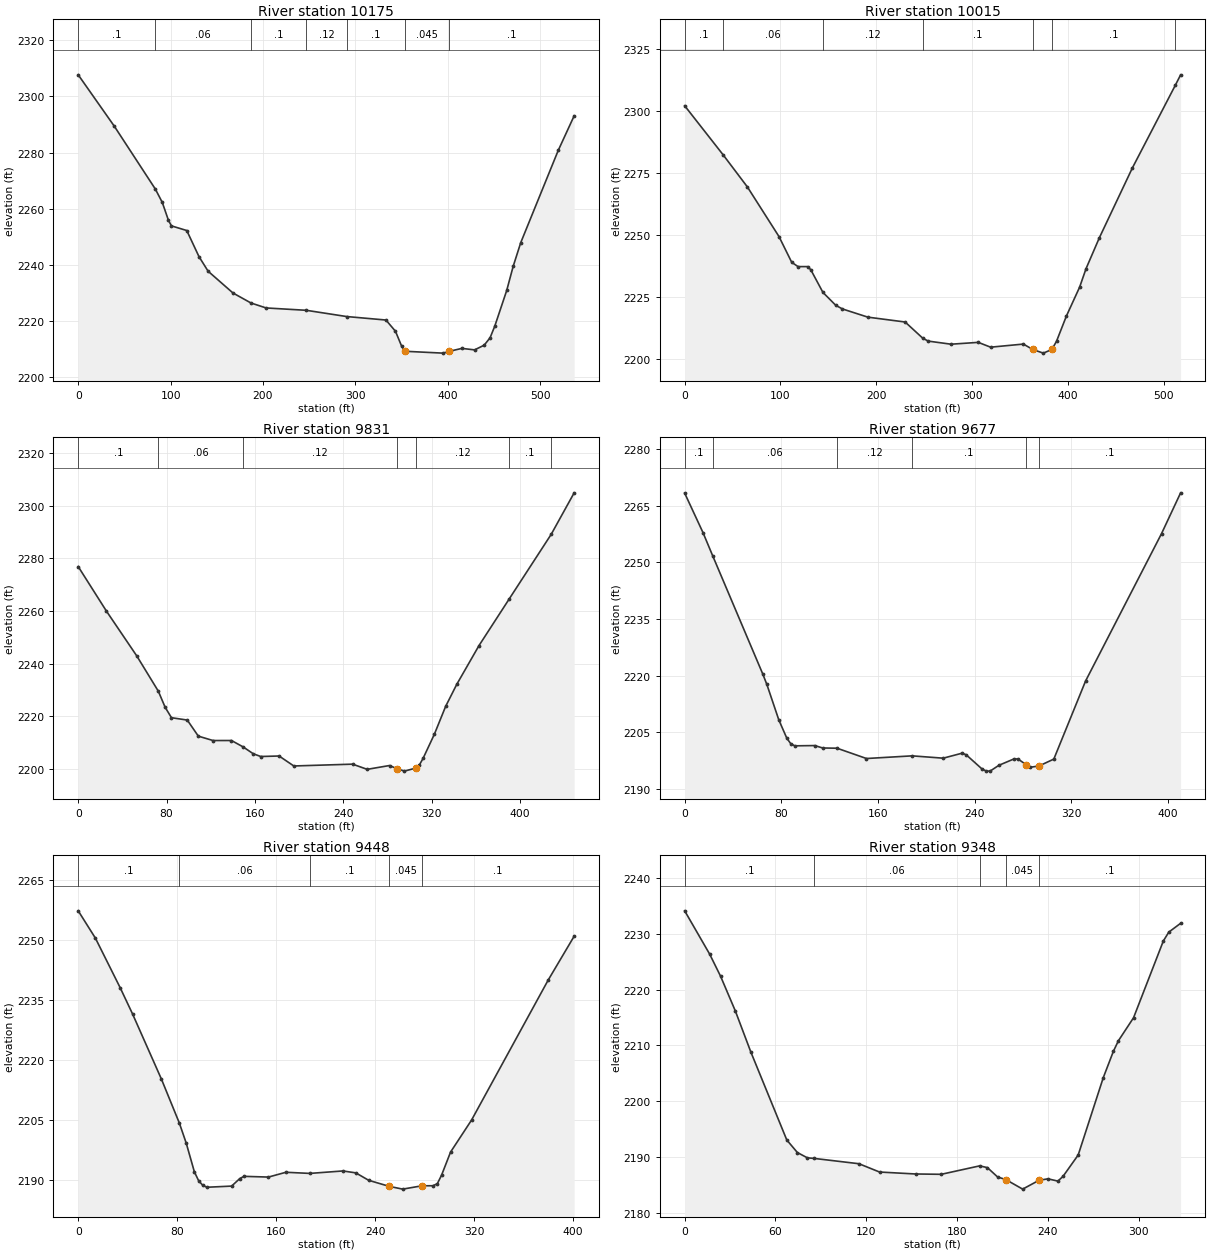
Type RM Length L Ch R = 1 ,10175   ,159.3,159.3,159.3
XS GIS Cut Line= 4
2189652.27943256299817.4223644292189964.00836824299856.388481389
2190080.90671912 299891.812224082190175.37003296299926.055175347
#Sta/Elev= 30
       0 2307.73    39.2 2289.33    83.52266.955      91  2262.2    97.6 2255.88
   100.9 2253.83   117.5 2252.17   130.7 2242.87   140.6 2237.65   167.5 2229.88
  187.01 2226.31   203.4 2224.54  246.92  2223.7  290.522221.476   333.1 2220.23
   343.4 2216.22   350.2  2210.8  353.932209.077   394.8 2208.42  401.822209.077
   415.3 2210.11     429 2209.58   439.4 2211.25   445.8  2213.9   450.9 2218.06
   463.8 2230.78   470.8 2239.39     479 2247.85   519.6 2280.78   536.8  2293.1
#Mann= 7 ,-1 , 0
       0      .1       0    83.5     .06       0  187.01      .1       0
  246.92     .12       0  290.52      .1       0  353.93    .045       0
  401.82      .1       0
Bank Sta=353.93,401.82
XS Rating Curve= 0 ,0
Exp/Cntr(USF)=0,0
Exp/Cntr=0.3,0.1

Type RM Length L Ch R = 1 ,10015   ,184.4,184.4,184.4
XS GIS Cut Line= 3
2189615.67489845299950.8517952312189875.44901151299988.637120767
2190118.69204465300065.388563264
#Sta/Elev= 30
       0 2302.24   40.152282.442    65.5 2269.47    98.4 2249.51   111.7 2239.11
   118.3 2237.37   128.3 2237.37   131.6 2236.12   144.3 2226.96   157.7 2221.75
   164.7 2220.28   191.2 2216.98   230.1 2215.02  248.442208.502   254.2 2207.32
     278 2206.07   306.4 2206.81   319.3 2204.87   353.5 2206.12  363.312203.934
   374.3 2202.47  383.232203.936   388.1 2207.27   398.4 2217.43   412.2 2229.09
   418.9 2236.55   432.8 2249.01   467.2 2277.13  512.072310.513   517.6 2314.72
#Mann= 7 ,-1 , 0
       0      .1       0   40.15     .06       0   144.3     .12       0
  248.44      .1       0  363.31    .045       0  383.23      .1       0
  512.07      .1       0
Bank Sta=363.31,383.23
XS Rating Curve= 0 ,0
Exp/Cntr(USF)=0,0
Exp/Cntr=0.3,0.1

Type RM Length L Ch R = 1 ,9831    ,154.2,154.2,154.2
XS GIS Cut Line= 4
2189615.67489845300140.9592143372189882.53376005300184.648496988
2189949.83887116300201.1795769112190056.11009924300225.976196794
#Sta/Elev= 30
       0 2276.89    25.5 2259.99      53 2242.92   72.492229.525    78.7 2223.37
    84.4 2219.44    98.7 2218.54   108.7 2212.43     122 2210.76   138.7 2210.77
  149.172208.354   158.5 2205.71   165.2 2204.69   181.8 2204.88   195.1 2201.09
   248.3 2201.78   261.5 2199.81   281.7 2201.26   288.5 2200.06   295.2 2199.13
  305.942200.336   308.7 2201.44   312.1 2203.99   322.3 2213.15   332.5 2223.74
   342.5 2232.07   362.7 2246.87  390.022264.582  428.022289.148   448.8 2304.93
#Mann= 7 ,-1 , 0
       0      .1       0   72.49     .06       0  149.17     .12       0
   288.5    .045       0  305.94     .12       0  390.02      .1       0
  428.02      .1       0
Bank Sta=288.5,305.94
XS Rating Curve= 0 ,0
Exp/Cntr(USF)=0,0
Exp/Cntr=0.3,0.1

Type RM Length L Ch R = 1 ,9677    ,229.1,229.1,229.1
XS GIS Cut Line= 4
2189589.69748714300310.9931792522189848.29080878300338.151381981
2189921.49987701300344.0553390962189998.25131951300347.597713365
#Sta/Elev= 30
       0 2268.34    15.2 2257.85   23.092251.806    64.6 2220.44      68 2217.66
    77.9 2208.26    84.5 2203.43    87.8 2201.96    91.1 2201.41   107.6 2201.48
   114.2 2200.84  126.03 2200.78   150.4 2198.05  188.182198.756   213.9 2198.14
   229.6 2199.47   232.9 2199.04   246.1 2195.25   249.7 2194.71   252.7 2194.72
     260 2196.26   272.5 2197.95   275.8 2197.92   282.3 2196.46     286 2195.74
  293.152196.075   305.4  2197.9   331.7  2218.6   394.5 2257.61   410.3 2268.42
#Mann= 6 ,-1 , 0
       0      .1       0   23.09     .06       0  126.03     .12       0
  188.18      .1       0   282.3    .045       0  293.15      .1       0
Bank Sta=282.3,293.15
XS Rating Curve= 0 ,0
Exp/Cntr(USF)=0,0
Exp/Cntr=0.3,0.1

Type RM Length L Ch R = 1 ,9448    ,99.5,99.5,99.5
XS GIS Cut Line= 4
2189564.90086726300499.9198069352189776.26253198300538.885923894
2189876.62980294300573.1288751622189953.38124543300595.563912199
#Sta/Elev= 30
       0 2257.36    13.9 2250.52    33.9 2238.12    43.9 2231.56    67.3  2215.2
   81.78  2204.2    87.3 2199.21    93.9 2192.01    97.3 2189.81   100.6 2188.66
     104 2188.15     124 2188.44   130.6 2190.32     134 2190.88   153.8  2190.7
   167.9  2191.9  187.262191.616     214 2192.23   224.4 2191.75   234.8 2189.89
   251.3 2188.38   262.3 2187.68   277.8 2188.51   286.8 2188.53   290.3 2189.05
   293.7 2191.16     301 2196.96     318 2204.99   379.9 2240.02   400.9    2251
#Mann= 5 ,-1 , 0
       0      .1       0   81.78     .06       0  187.26      .1       0
   251.3    .045       0   277.8      .1       0
#XS Ineff= 2 , 0
          159.43 2191.02
Permanent Ineff=
       F       F
Bank Sta=251.3,277.8
XS Rating Curve= 0 ,0
Exp/Cntr(USF)=0,0
Exp/Cntr=0.3,0.1

Type RM Length L Ch R = 1 ,9348    ,140.1,140.1,140.1
XS GIS Cut Line= 3
2189579.07036433300593.2023293532189767.99699202300645.157151966
2189897.88404855300667.592189004
#Sta/Elev= 30
       0 2234.17    16.5  2226.4    23.7 2222.44    33.5 2216.18    43.7 2208.84
    67.5 2193.02    74.5 2190.77    81.1 2189.82   85.752189.709   115.2 2188.76
   128.8 2187.27   152.6 2186.92   169.6 2186.86  194.982188.377   200.1 2188.06
   206.8 2186.39  212.322185.908   223.4  2184.2   234.1 2185.77   240.1 2186.05
   246.7 2185.64   250.1  2186.5   260.1 2190.33   276.7 2204.23   283.4 2208.97
   286.7 2210.85   296.7 2214.98   316.4 2228.77     320 2230.35   327.8 2231.93
#Mann= 5 ,-1 , 0
       0      .1       0   85.75     .06       0  194.98      .1       0
  212.32    .045       0   234.1      .1       0
Bank Sta=212.32,234.1
XS Rating Curve= 0 ,0
Exp/Cntr(USF)=0,0
Exp/Cntr=0.3,0.1

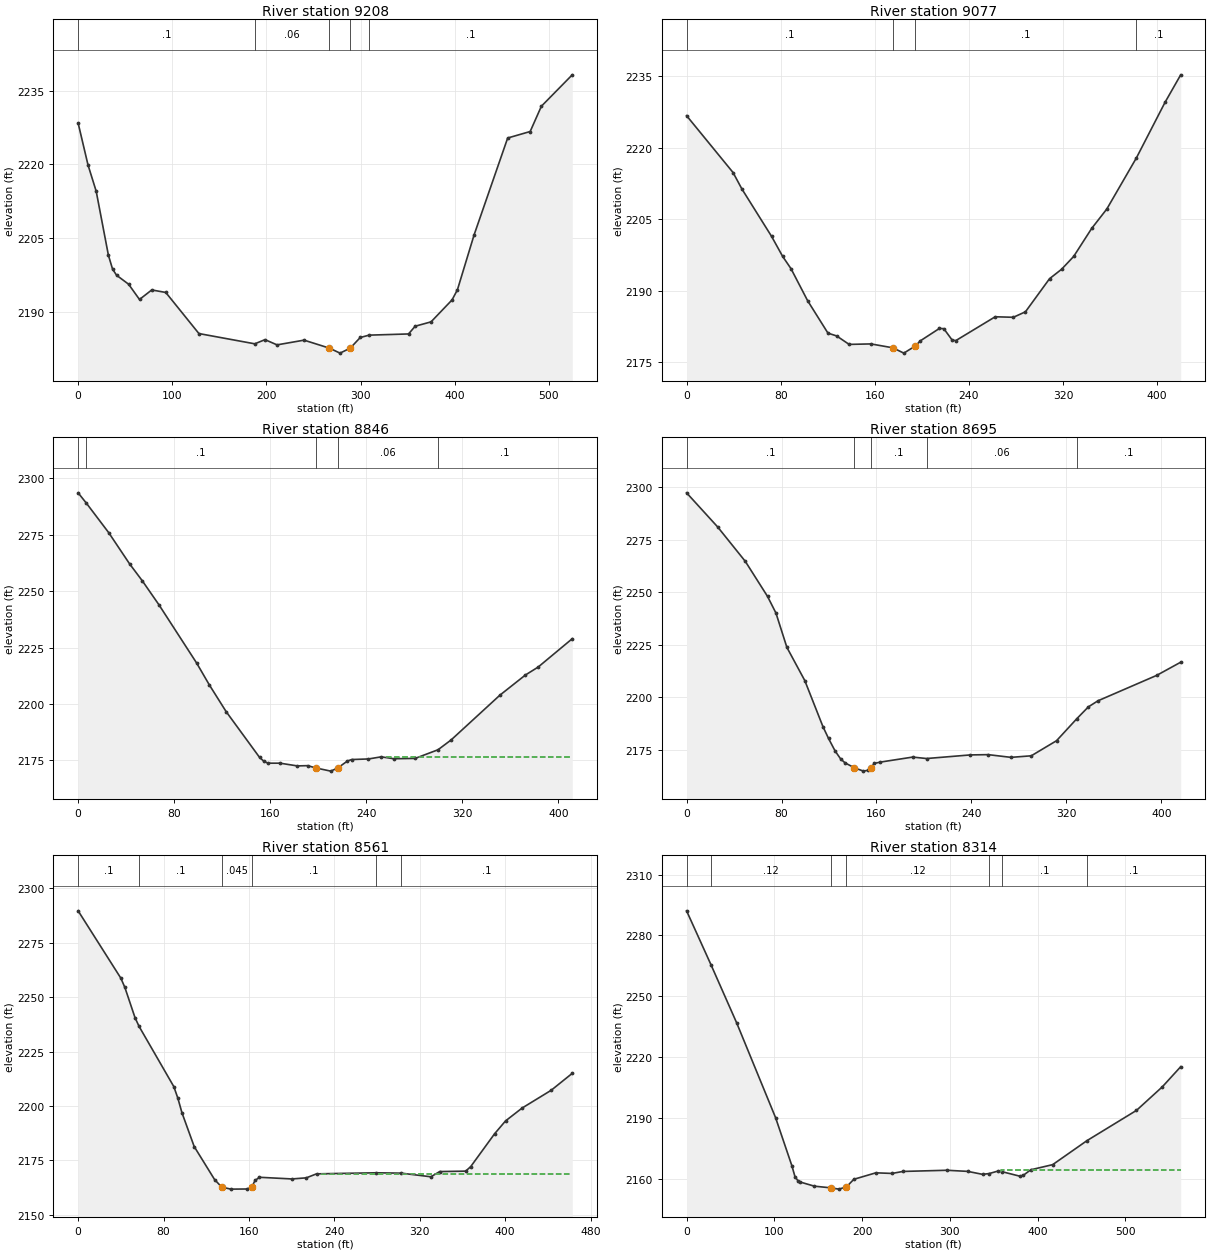
Type RM Length L Ch R = 1 ,9208    ,130.8,130.8,130.8
XS GIS Cut Line= 4
2189560.17770157300605.0102435832189697.14950664300763.236294268
2189837.66368598300811.6487426122189976.99707389300719.547011616
#Sta/Elev= 30
       0 2228.38    10.5 2219.86    19.2 2214.51    32.2 2201.47    36.6 2198.67
    40.9 2197.42    53.6 2195.61    65.2  2192.5    78.2 2194.44    93.1 2193.93
   128.3 2185.57  187.642183.484   198.5 2184.33   211.3 2183.27     240 2184.23
     267  2182.6   278.2 2181.59  289.04  2182.6   299.7 2184.77  309.122185.248
     351 2185.49     358 2187.06   374.9 2187.95   397.2 2192.41   402.9 2194.46
   420.7 2205.68   456.3 2225.34   480.2 2226.66   492.1  2231.8   524.9 2238.19
#Mann= 5 ,-1 , 0
       0      .1       0  187.64     .06       0     267    .045       0
  289.04     .06       0  309.12      .1       0
Bank Sta=267,289.04
XS Rating Curve= 0 ,0
Exp/Cntr(USF)=0,0
Exp/Cntr=0.3,0.1

Type RM Length L Ch R = 1 ,9077    ,231.9,231.9,231.9
XS GIS Cut Line= 4
2189522.39237603300808.1063683432189652.27943256300860.061190956
2189739.65799787 300932.089467762189896.70325713300988.767456065
#Sta/Elev= 30
       0 2226.67    39.5 2214.76      47 2211.32    72.3 2201.36    81.7 2197.17
    88.8  2194.6   102.9  2187.9   120.2  2181.1   127.6 2180.51   138.2 2178.74
   156.7 2178.84   175.3 2178.03   184.7 2176.91  194.492178.408   198.7 2179.48
     215 2182.09   218.7 2182.03   225.9 2179.61     229 2179.55   262.4 2184.53
   277.8 2184.42   288.1 2185.57   308.6 2192.51   318.8 2194.48   329.1 2197.17
   344.4 2203.04   357.3 2207.12  382.462217.834   406.8 2229.48   420.1 2235.23
#Mann= 4 ,-1 , 0
       0      .1       0   175.3    .045       0  194.49      .1       0
  382.46      .1       0
Bank Sta=175.3,194.49
XS Rating Curve= 0 ,0
Exp/Cntr(USF)=0,0
Exp/Cntr=0.3,0.1

Type RM Length L Ch R = 1 ,8846    ,151,151,151
XS GIS Cut Line= 3
2189439.73697642301025.3719901782189665.26813821301106.846598367
2189824.67498032 301170.60933521
#Sta/Elev= 30
       0 2293.64    6.87 2289.06    25.5 2275.95    42.9  2262.1    53.4 2254.65
    67.4  2243.9    98.8 2218.05   109.2  2208.5   123.2 2196.64   151.1 2176.28
   154.6  2174.6   158.1 2173.71   168.1 2173.72   182.5 2172.51   191.2 2172.62
  197.812171.613   210.4 2170.19  216.252171.613   224.3 2174.68   227.8 2175.33
   241.8 2175.59   252.4 2176.53     263 2175.68   280.7 2175.84  299.722179.668
   310.6 2184.01   351.3 2203.91   372.5 2212.83   383.1 2216.35   411.5 2228.93
#Mann= 5 ,-1 , 0
       0      .1       0    6.87      .1       0  197.81    .045       0
  216.25     .06       0  299.72      .1       0
#XS Ineff= 2 , 0
                          256.01         2176.33
Permanent Ineff=
       F       F
Bank Sta=197.81,216.25
XS Rating Curve= 0 ,0
Exp/Cntr(USF)=0,0
Exp/Cntr=0.3,0.1

Type RM Length L Ch R = 1 ,8695    ,133.7,133.7,133.7
XS GIS Cut Line= 3
 2189423.2058965301086.7731441752189584.97432145301246.179986283
 2189746.7427464301344.185674394
#Sta/Elev= 30
       0  2297.2    26.1 2281.05    49.5 2264.63    68.2    2248    75.3 2240.09
    84.5  2223.8    99.6 2208.02   114.9 2186.13   119.6 2180.54   125.1 2174.61
   129.8  2170.8   133.6  2168.9  141.412166.597     149 2165.01     153 2165.45
  155.05  2166.6   158.2 2168.65   162.8 2169.26   190.5 2171.68  202.242170.995
   239.1 2172.71   254.1 2172.84   273.3 2171.55   290.4 2172.29   311.7 2179.46
  328.76 2189.91   338.5 2195.53   346.6 2198.42   396.1  2210.5   416.3 2216.75
#Mann= 5 ,-1 , 0
       0      .1       0  141.41    .045       0  155.05      .1       0
  202.24     .06       0  328.76      .1       0
#XS Ineff= 2 , 0
                           253.4         2172.76
Permanent Ineff=
       F       F
Bank Sta=141.41,155.05
XS Rating Curve= 0 ,0
Exp/Cntr(USF)=0,0
Exp/Cntr=0.3,0.1

Type RM Length L Ch R = 1 ,8561    ,247,247,247
XS GIS Cut Line= 3
2189342.91207973301136.3663839422189457.44884776301328.835385895
2189610.95173276301511.858056463
#Sta/Elev= 30
       0 2289.59      40 2258.69    43.8 2254.41    53.3 2240.54   57.082236.554
    89.6 2208.93    93.4 2203.63    97.2 2196.99   108.7 2181.41   127.8 2166.26
  134.452162.798     143 2161.86   158.3 2161.92  162.422162.794   165.8 2165.84
   169.8  2167.3   200.3 2166.53   213.7 2167.04   223.3 2168.87  279.092169.357
  302.582169.196   330.4 2167.53   338.7 2169.92     363 2170.12   367.7  2172.2
   390.1 2187.29   400.3 2193.16   415.8 2199.06   443.1 2207.24   462.8    2215
#Mann= 6 ,-1 , 0
       0      .1       0   57.08      .1       0  134.45    .045       0
  162.42      .1       0  279.09     .06       0  302.58      .1       0
#XS Ineff= 2 , 0
                          227.73         2168.93
Permanent Ineff=
       F       F
Bank Sta=134.45,162.42
XS Rating Curve= 0 ,0
Exp/Cntr(USF)=0,0
Exp/Cntr=0.3,0.1

Type RM Length L Ch R = 1 ,8314    ,252.8,252.8,252.8
XS GIS Cut Line= 3
2189123.28487505301224.9257406692189230.73689454301433.925822543
2189432.65222788301692.519144185
#Sta/Elev= 30
       0 2292.14   27.762265.638    57.1 2236.94   101.4 2190.29     120 2166.59
   123.5 2161.25   127.2 2159.01   129.7 2158.54   145.6 2156.53   164.1 2155.71
   173.6 2155.07  182.212156.177   190.6 2159.91   215.7  2163.1   234.2  2162.8
   246.5 2163.78   296.5 2164.36   320.4 2163.81   337.3 2162.35  344.74 2162.73
   354.8 2163.96  359.262163.685   379.7 2161.45   383.9 2161.93   392.2 2164.59
   417.2 2167.13  456.372178.977   512.7 2193.85   542.1 2205.43   563.1 2215.37
#Mann= 7 ,-1 , 0
       0      .1       0   27.76     .12       0   164.1    .045       0
  182.21     .12       0  344.74     .06       0  359.26      .1       0
  456.37      .1       0
#XS Ineff= 2 , 0
                          358.57         2164.32
Permanent Ineff=
       F       F
Bank Sta=164.1,182.21
XS Rating Curve= 0 ,0
Exp/Cntr(USF)=0,0
Exp/Cntr=0.3,0.1

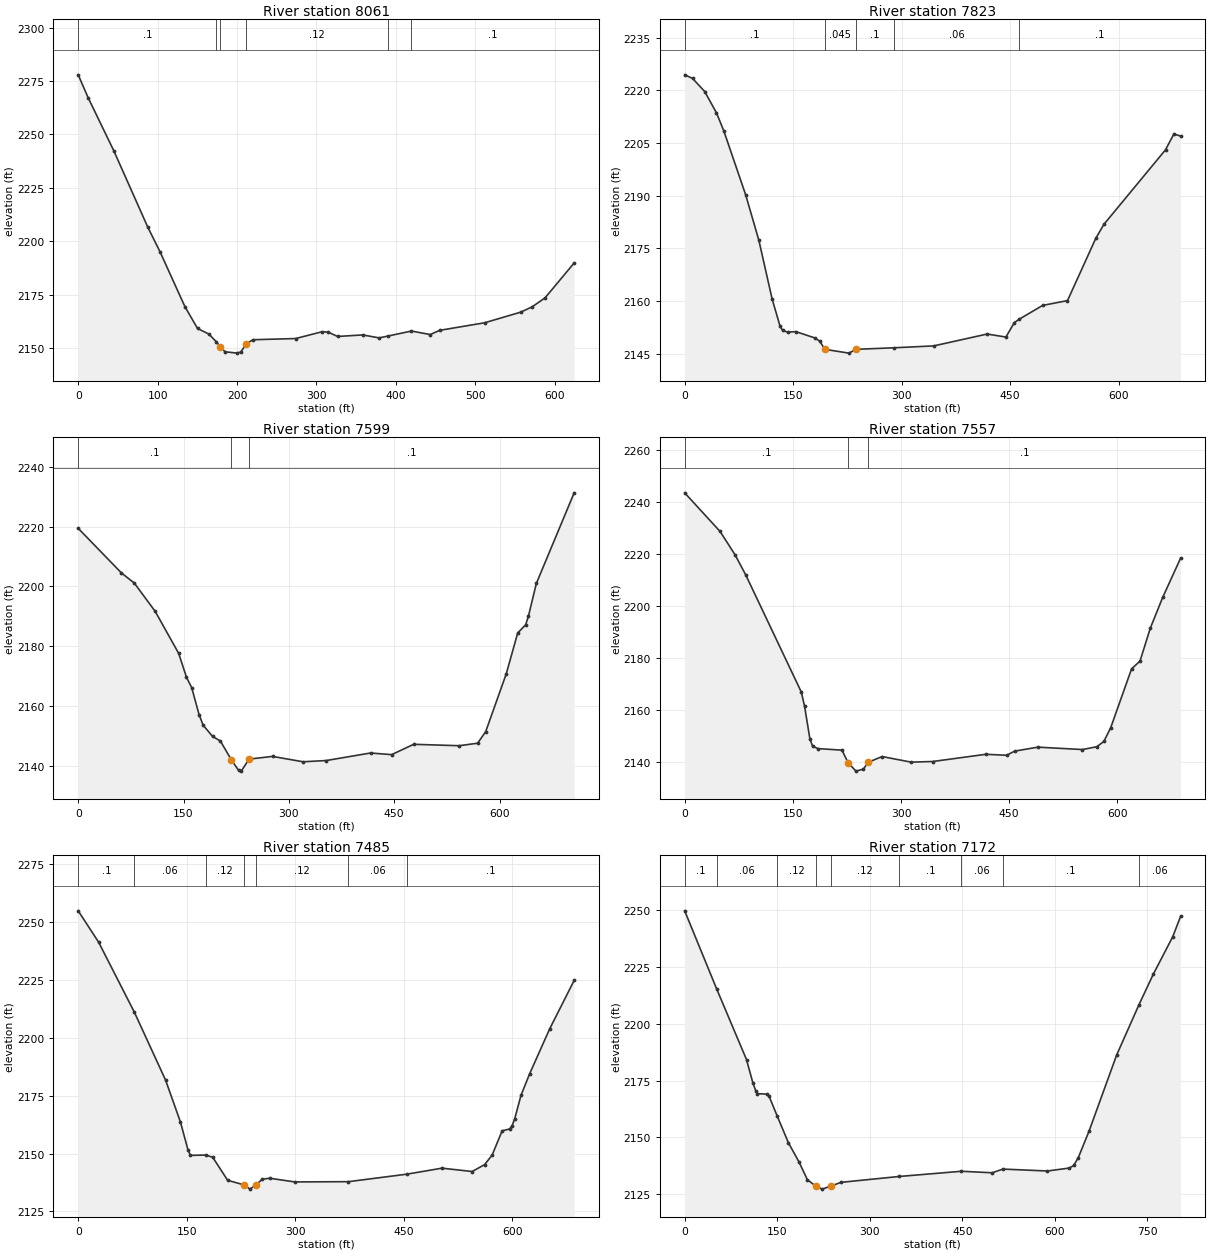
Type RM Length L Ch R = 1 ,8061    ,238.2,238.2,238.2
XS GIS Cut Line= 3
2188874.13788479301326.4738030482189021.73681267 301557.90892196
2189223.65214601301843.660446331
#Sta/Elev= 30
       0 2277.86    12.4 2267.23    44.8 2242.32    87.6 2206.55   103.2 2194.88
   134.3 2169.38   150.2 2159.15   164.5 2156.51  174.032152.837   178.7  2150.6
   184.9 2148.21   200.5 2147.59   204.9 2148.22   211.8 2152.03   219.9 2153.86
   273.8 2154.42     307  2157.6   314.6 2157.43   326.6 2155.39   358.2 2156.11
   378.9 2154.72  389.512155.547  419.572157.925   443.3 2156.28     455 2158.25
   511.7  2161.8   557.2 2166.78   571.7  2169.3   587.8 2173.48   624.4 2189.79
#Mann= 6 ,-1 , 0
       0      .1       0  174.03     .12       0   178.7    .045       0
   211.8     .12       0  389.51     .06       0  419.57      .1       0
Bank Sta=178.7,211.8
XS Rating Curve= 0 ,0
Exp/Cntr(USF)=0,0
Exp/Cntr=0.3,0.1

Type RM Length L Ch R = 1 ,7823    ,224.5,224.5,224.5
XS GIS Cut Line= 3
2188698.19996276301439.8297796582188828.08701929301700.784684146
2189037.08710117 302034.94865686
#Sta/Elev= 30
       0 2224.42    10.9  2223.4    27.7 2219.66    43.9 2213.61      54 2208.51
    84.2  2190.3   102.5 2177.32   120.8 2160.63   131.8 2152.83   135.3 2151.61
   142.3 2151.11   153.8 2151.25   179.8 2149.47   186.8 2148.52   193.82146.212
   227.1 2145.13  236.712146.212  288.722146.648   344.3 2147.19   418.1 2150.57
   444.1 2149.71   455.7 2153.82  462.862154.839   494.9 2158.73   529.2 2160.09
   568.3 2177.82   579.5 2181.81   664.7 2203.06   676.3 2207.56   685.6 2206.97
#Mann= 5 ,-1 , 0
       0      .1       0   193.8    .045       0  236.71      .1       0
  288.72     .06       0  462.86      .1       0
Bank Sta=193.8,236.71
XS Rating Curve= 0 ,0
Exp/Cntr(USF)=0,0
Exp/Cntr=0.3,0.1

Type RM Length L Ch R = 1 ,7599    ,41.7,41.7,41.7
XS GIS Cut Line= 3
2188497.95844071301549.5161927972188713.68607779301957.001729498
2188837.76471872302168.499412907
#Sta/Elev= 30
       0 2219.44    61.4 2204.54      80 2201.08   109.7 2191.61   143.1 2177.56
   154.2 2169.56   161.6 2166.11   172.1 2157.08   177.9 2153.52   191.3 2149.78
   202.5 2148.22   218.2 2141.88   228.4 2138.39   232.2 2138.14   243.3 2142.16
   276.7 2143.07   320.2 2141.27   353.2 2141.69   416.3 2144.21   446.4 2143.66
   477.7 2147.12   542.5 2146.65   568.8 2147.49   580.3 2151.35   609.6 2170.72
   625.9 2184.39   637.3 2187.18   641.1 2189.94   652.5 2201.01   706.3 2231.33
#Mann= 3 , 0 , 0
       0      .1       0   218.2    .045       0   243.3      .1       0
Bank Sta=218.2,243.3
XS Rating Curve= 0 ,0
Exp/Cntr(USF)=0,0
Exp/Cntr=0.5,0.3

Type RM Length L Ch R = 1 ,7557    ,72.2,72.2,72.2
XS GIS Cut Line= 4
 2188459.8888577301565.0260229132188598.06734419 301827.28315034
  2188668.566572301986.6114051752188758.80558358302184.009243024
#Sta/Elev= 30
       0  2243.4    49.1 2228.54    69.8  2219.6    84.5 2211.93   161.7 2166.81
   166.2 2161.41   173.6 2148.85   177.3    2146   184.7 2145.04   218.1 2144.45
   226.62139.643   237.5 2136.38   247.8 2137.15   254.5 2139.78   273.7 2141.99
   313.9 2139.84   343.9 2140.08   417.6 2142.85   446.7 2142.48   457.4 2144.06
   489.8  2145.6   551.6 2144.68   571.4 2145.76   581.3  2147.8   590.8 2153.11
   619.7 2175.72   631.4  2178.7   645.6 2191.31   662.9 2203.22   687.7  2218.3
#Mann= 3 , 0 , 0
       0      .1       0   226.6    .045       0   254.5      .1       0
Bank Sta=226.6,254.5
XS Rating Curve= 0 ,0
Exp/Cntr(USF)=0,0
Exp/Cntr=0.5,0.3

Type RM Length L Ch R = 1 ,7485    ,312.9,312.9,312.9
XS GIS Cut Line= 3
2188436.06426685301576.8015847292188517.53887504301843.660446331
2188645.06434873302229.779241658
#Sta/Elev= 30
       0 2254.71    28.2 2241.19   77.742210.914   120.8 2181.68   141.4 2163.55
   151.7 2151.66   155.1 2149.21  176.252149.346     186 2148.39   206.6 2138.46
  229.812136.427   237.5 2134.65  245.432136.425   254.6 2138.95   264.9 2139.34
   299.3 2137.76  373.592137.863  454.392141.104   502.9 2143.69   544.7 2142.25
   561.9 2145.23   572.3 2149.34   586.1 2159.79   596.5 2160.61   599.9 2161.97
   603.4 2164.87   612.2  2175.1   624.1 2184.37   651.8 2203.75   685.7 2224.69
#Mann= 7 ,-1 , 0
       0      .1       0   77.74     .06       0  176.25     .12       0
  229.81    .045       0  245.43     .12       0  373.59     .06       0
  454.39      .1       0
Bank Sta=229.81,245.43
XS Rating Curve= 0 ,0
Exp/Cntr(USF)=0,0
Exp/Cntr=0.3,0.1

Type RM Length L Ch R = 1 ,7172    ,304.8,304.8,304.8
XS GIS Cut Line= 3
2188142.15788484301648.3216227012188221.34523831301934.475922747
2188424.71275973302398.801768104
#Sta/Elev= 30
       0 2249.71   51.862215.311   100.2 2184.21   110.4 2174.09   115.3 2170.35
   117.9 2169.22   134.2 2168.98   136.6 2168.22  150.032159.304   168.2 2147.55
   185.3 2139.14   198.9 2131.31   212.32128.522   222.7 2127.17  237.122128.523
   253.3 2130.16  347.732132.743   448.62135.034   498.4 2134.37  515.772135.999
     588 2135.15   623.6 2136.47   630.4 2137.59   637.9 2140.99   655.3 2152.65
   700.1  2186.2   736.3 2208.37   759.7 2221.91     791 2238.29   803.8 2247.29
#Mann= 9 ,-1 , 0
       0      .1       0   51.86     .06       0  150.03     .12       0
   212.3    .045       0  237.12     .12       0  347.73      .1       0
   448.6     .06       0  515.77      .1       0   736.3     .06       0
Bank Sta=212.3,237.12
XS Rating Curve= 0 ,0
Exp/Cntr(USF)=0,0
Exp/Cntr=0.3,0.1

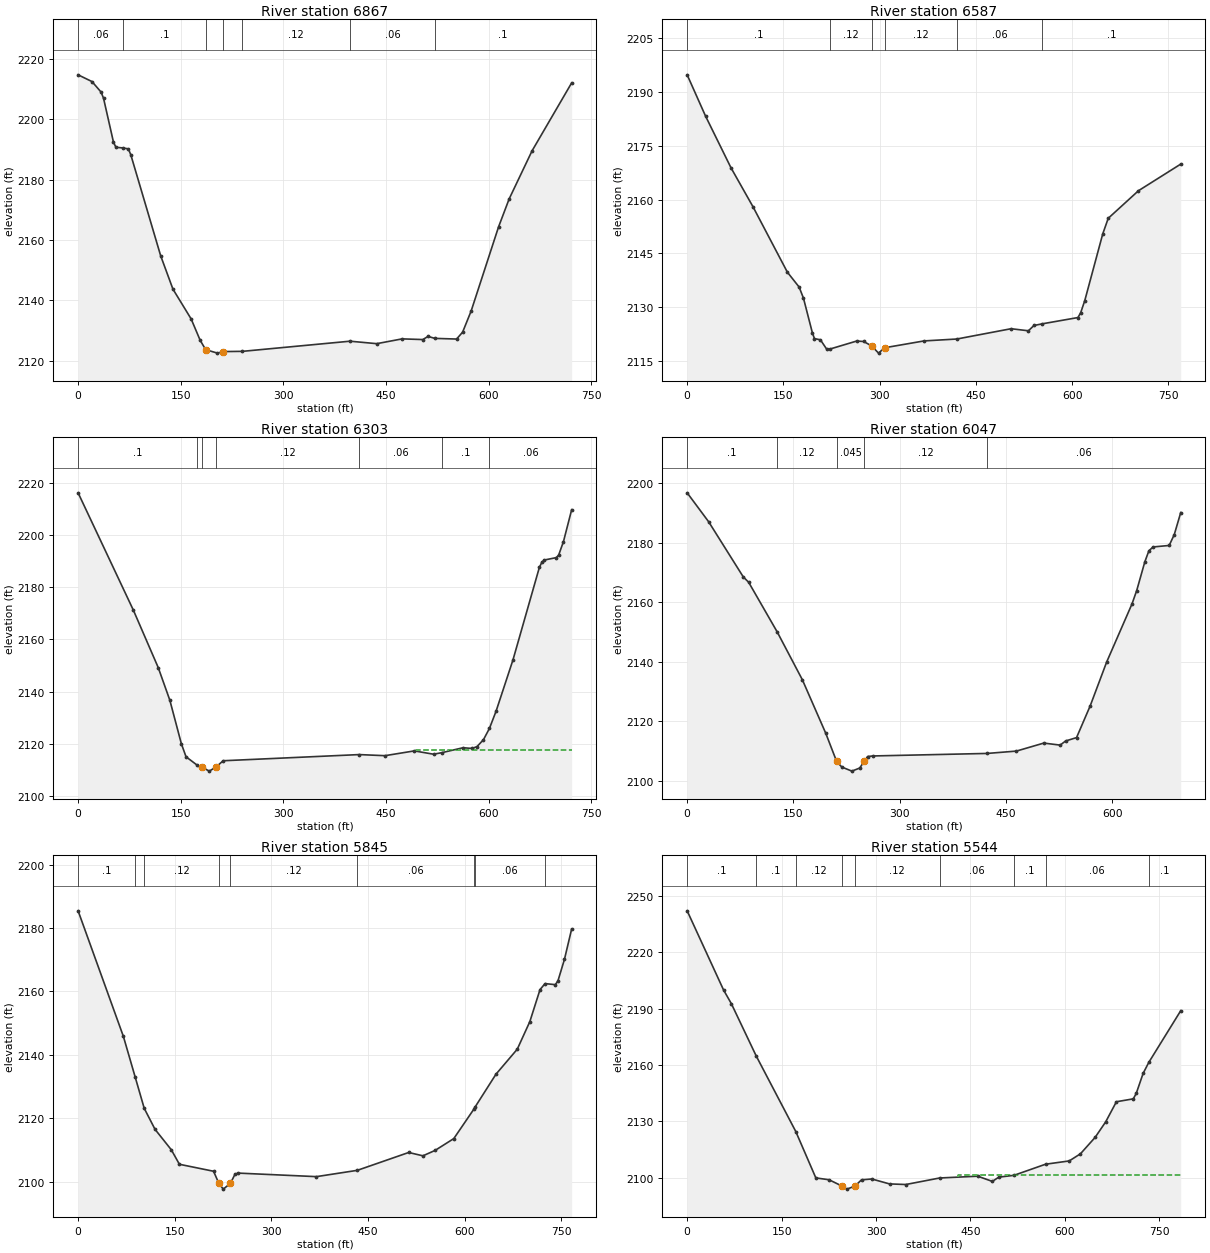
Type RM Length L Ch R = 1 ,6867    ,279.7,279.7,279.7
XS GIS Cut Line= 3
2187834.40703385301783.3000661182187945.98921374302022.661839113
2188161.95472321302425.797456788
#Sta/Elev= 30
       0 2214.66    20.3 2212.43    33.6 2208.95    37.2 2206.89    51.7 2192.39
    55.3 2190.67   65.612190.465    73.4 2190.15      77 2188.23   120.7 2154.77
   138.6 2143.74   165.2 2133.88   178.4 2126.81  186.442123.703   203.7 2122.55
   212.1 2123.06  240.292123.141  397.462126.499   436.5 2125.68   473.7 2127.27
   503.9 2127.04   511.5 2128.09  521.362127.431   553.2 2127.21     562 2129.49
   574.5  2136.5   614.5  2164.3     630 2173.58   663.5  2189.5   721.4    2212
#Mann= 7 ,-1 , 0
       0     .06       0   65.61      .1       0  186.44    .045       0
   212.1      .1       0  240.29     .12       0  397.46     .06       0
  521.36      .1       0
Bank Sta=186.44,212.1
XS Rating Curve= 0 ,0
Exp/Cntr(USF)=0,0
Exp/Cntr=0.3,0.1

Type RM Length L Ch R = 1 ,6587    ,284,284,284
XS GIS Cut Line= 4
2187580.64756022301873.2856950642187665.23405143302047.857815218
2187771.41709359302235.0279234242188003.58001627302510.383947996
#Sta/Elev= 30
       0 2194.84    28.6 2183.33    68.3 2168.87   102.7 2157.95   156.2  2139.7
   174.5 2135.55   181.3 2132.43   195.2 2122.74   198.4 2121.15   207.7 2120.81
   217.6 2118.17  222.392118.222   264.3 2120.47     275 2120.34   287.4 2119.13
   298.3 2117.09  307.722118.588   369.2  2120.5  420.362121.032   504.9 2123.91
   531.9 2123.33   540.5 2124.81  553.732125.285   609.1 2127.03   613.4  2128.4
   619.7 2131.75   647.7 2150.37   656.3 2154.76   703.4 2162.46   769.3  2169.9
#Mann= 6 ,-1 , 0
       0      .1       0  222.39     .12       0   287.4    .045       0
  307.72     .12       0  420.36     .06       0  553.73      .1       0
Bank Sta=287.4,307.72
XS Rating Curve= 0 ,0
Exp/Cntr(USF)=0,0
Exp/Cntr=0.3,0.1

Type RM Length L Ch R = 1 ,6303    ,256.1,256.1,256.1
XS GIS Cut Line= 3
2187407.87515265301979.4687372192187476.26423065302236.827636003
2187640.03807533302661.559804624
#Sta/Elev= 30
       0 2216.06    80.8 2171.17   117.1 2149.23   134.1 2136.73     151 2120.03
   157.8 2115.08  174.452111.791  180.432111.184   191.8 2109.59  201.672111.184
   212.1 2113.56  410.922115.919   448.6  2115.5   491.5 2117.33   519.6 2116.06
  531.53 2116.64   562.8 2118.54   575.9 2118.27   583.1 2118.97   592.6 2121.63
  601.322125.948     611 2132.52   635.7 2152.14   674.3 2187.54   677.9 2189.48
   681.4 2190.35     699 2191.27   702.5 2192.25   709.5  2197.4   721.5 2209.61
#Mann= 7 ,-1 , 0
       0      .1       0  174.45     .12       0  180.43    .045       0
  201.67     .12       0  410.92     .06       0  531.53      .1       0
  601.32     .06       0
#XS Ineff= 2 , 0
                          493.54         2117.52
Permanent Ineff=
       F       F
Bank Sta=180.43,201.67
XS Rating Curve= 0 ,0
Exp/Cntr(USF)=0,0
Exp/Cntr=0.3,0.1

Type RM Length L Ch R = 1 ,6047    ,201.9,201.9,201.9
XS GIS Cut Line= 4
2187143.31740355302105.448617743 2187233.3030325302267.422749844
2187290.89383502302377.2052171572187494.26135644302706.552619097
#Sta/Elev= 30
       0  2196.8    30.4 2187.04    79.2 2168.51    86.7 2166.74  126.992150.034
   162.5 2133.94   195.4 2116.01   210.9 2106.45   218.2 2104.58   232.4 2103.21
   243.5 2104.26   249.8 2106.55   254.6 2108.12   261.8 2108.31  423.32 2109.16
   464.5 2109.95   503.1 2112.64   526.2 2111.96   533.9 2113.35   549.3 2114.48
   568.6 2125.17   591.8  2139.9   627.6 2159.47   634.2 2163.95   645.7 2173.64
   651.4 2177.32   657.3  2178.6     680  2179.1   687.2 2182.77   696.3 2190.17
#Mann= 5 ,-1 , 0
       0      .1       0  126.99     .12       0   210.9    .045       0
   249.8     .12       0  423.32     .06       0
Bank Sta=210.9,249.8
XS Rating Curve= 0 ,0
Exp/Cntr(USF)=0,0
Exp/Cntr=0.3,0.1

Type RM Length L Ch R = 1 ,5845    ,300.8,300.8,300.8
XS GIS Cut Line= 3
2186961.54643308302199.033671846 2187121.7208526302477.989121576
2187371.88090107302845.130487672
#Sta/Elev= 30
       0 2185.44    70.3  2145.8    88.5 2133.05  102.632123.115   119.4 2116.49
   144.7 2110.03   157.2 2105.47   210.2 2103.27  218.362099.474   225.3 2097.63
  236.462099.475   243.3 2102.26     248 2102.69   369.8 2101.57   433.3 2103.56
     513 2109.19   535.1 2108.14     554 2109.85     583 2113.58  614.662123.019
  616.272123.615   648.4 2133.88   681.5 2141.79     701 2150.49   716.8 2160.59
   724.62162.474   740.5 2162.15   744.6 2163.33   754.7 2170.13   765.9 2179.73
#Mann= 9 ,-1 , 0
       0      .1       0    88.5      .1       0  102.63     .12       0
  218.36    .045       0  236.46     .12       0   433.3     .06       0
  614.66      .1       0  616.27     .06       0   724.6      .1       0
Bank Sta=218.36,236.46
XS Rating Curve= 0 ,0
Exp/Cntr(USF)=0,0
Exp/Cntr=0.3,0.1

Type RM Length L Ch R = 1 ,5544    ,332.9,332.9,332.9
XS GIS Cut Line= 3
2186693.38925882302388.003492631 2186925.5521815302690.355205887
2187181.11136771303001.705482037
#Sta/Elev= 30
       0 2242.03    57.8 2199.91    70.2 2192.61  109.712164.755  172.522124.571
   204.4 2099.87   225.5 2098.88  246.372095.455   253.6  2093.9  266.142095.456
     277 2098.85   293.3 2099.29   321.4 2096.68   347.3 2096.36  401.07 2099.83
   461.5 2100.78   484.8 2098.01     495 2100.28  518.992101.234  569.31 2107.16
   606.9 2108.91   624.7  2112.7     648 2121.44   664.8 2129.71   681.8 2140.41
   708.6 2141.95   713.3  2144.8   724.2 2155.46  733.192161.318     784 2188.87
#Mann= 9 ,-1 , 0
       0      .1       0  109.71      .1       0  172.52     .12       0
  246.37    .045       0  266.14     .12       0  401.07     .06       0
  518.99      .1       0  569.31     .06       0  733.19      .1       0
#XS Ineff= 2 , 0
                          430.56         2101.26
Permanent Ineff=
       F       F
Bank Sta=246.37,266.14
XS Rating Curve= 0 ,0
Exp/Cntr(USF)=0,0
Exp/Cntr=0.3,0.1