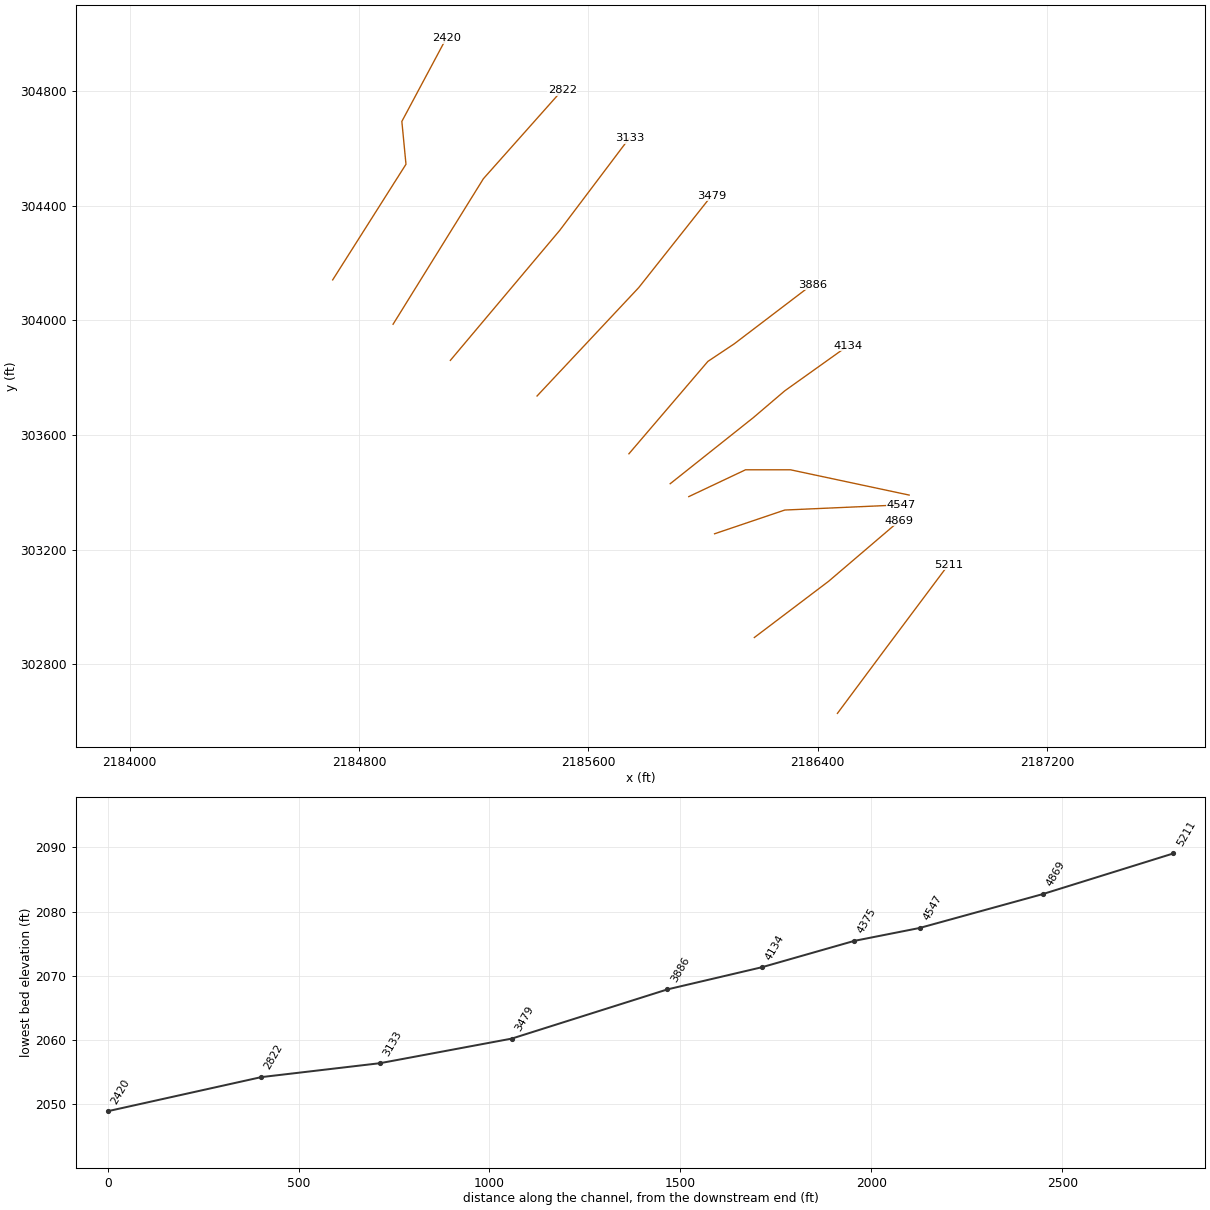
HEC-RAS study SLPHRLCKRN.prj: SLPHRLCKRN

--- SLPHRLCKRN.g01 (geometry) --- (continued)

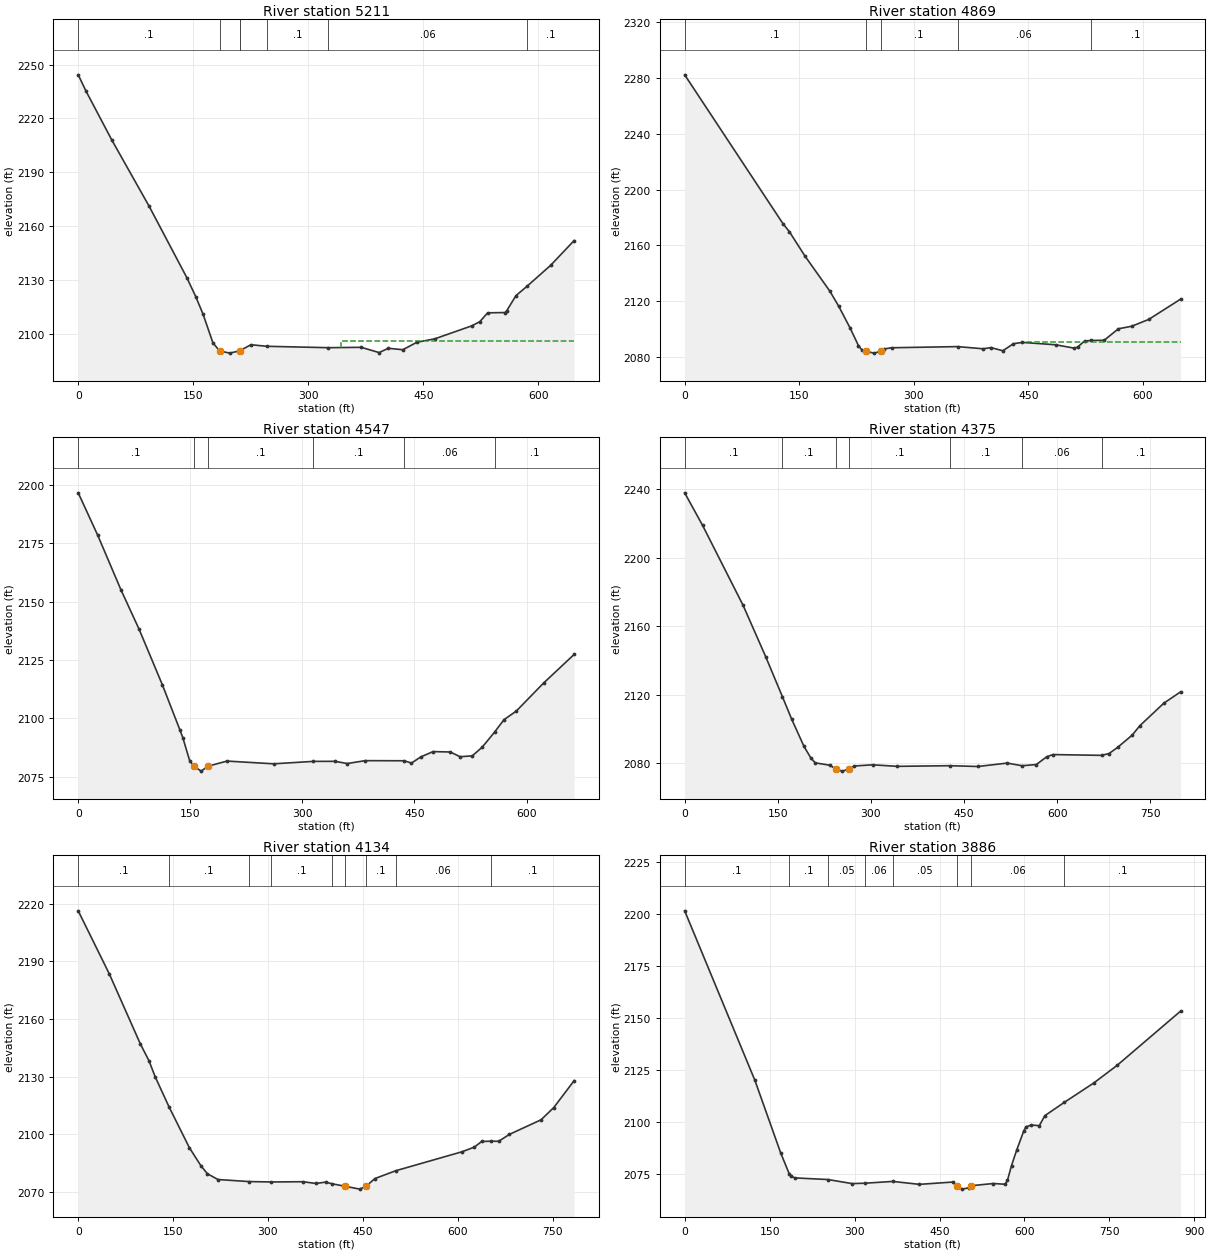
Type RM Length L Ch R = 1 ,5211    ,342.6,342.6,342.6
XS GIS Cut Line= 3
2186468.42518646302629.164978204 2186635.7984563302854.129050567
2186855.36339093303147.482200929
#Sta/Elev= 30
       0 2244.33    10.4 2235.05    43.8 2207.98    92.5 2171.02   141.7 2131.15
   153.4 2120.49   162.8 2110.83   175.7  2094.8  184.442090.293   197.7 2089.08
   210.4 2090.36  211.26 2090.51   225.2 2093.77  245.952092.887  326.412092.113
   369.1 2092.32   392.5 2089.38   404.3 2091.78   423.4 2090.98   441.8 2095.15
   465.2 2097.08   513.5 2104.34   523.8 2106.65     534 2111.56   556.6 2111.72
   558.6 2112.52   570.9 2121.16  585.192126.325     616 2138.01   646.8 2151.89
#Mann= 7 ,-1 , 0
       0      .1       0  184.44    .045       0   210.4      .1       0
  211.26     .12       0  245.95      .1       0  326.41     .06       0
  585.19      .1       0
#XS Ineff= 2 , 0
                          342.11         2095.82
Permanent Ineff=
       F       F
Bank Sta=184.44,210.4
XS Rating Curve= 0 ,0
Exp/Cntr(USF)=0,0
Exp/Cntr=0.3,0.1

Type RM Length L Ch R = 1 ,4869    ,322.2,322.2,322.2
XS GIS Cut Line= 3
2186178.67146126302893.7227273032186437.83007262303089.891398404
2186684.39069593303300.457770135
#Sta/Elev= 30
       0  2282.4   128.7  2175.6     137 2169.94   157.5 2152.36     190 2127.26
   201.7 2116.36   216.5 2100.84   227.5 2088.15   231.6 2085.29  236.862084.097
   248.1 2082.74  256.762084.095   260.4 2085.68   270.8 2086.59  357.192087.421
   390.9 2085.85     401 2086.72   416.5 2084.45   430.5 2089.52   442.1 2090.43
   485.9 2088.73   510.1  2086.3   514.3 2087.04   523.6 2091.47   532.12091.823
   549.2 2091.95   567.8  2100.2   585.2 2102.02   607.4 2106.88   649.3 2121.48
#Mann= 5 ,-1 , 0
       0      .1       0  236.86    .045       0  256.76      .1       0
  357.19     .06       0   532.1      .1       0
#XS Ineff= 2 , 0
                          447.65         2090.83
Permanent Ineff=
       F       F
Bank Sta=236.86,256.76
XS Rating Curve= 0 ,0
Exp/Cntr(USF)=0,0
Exp/Cntr=0.3,0.1

Type RM Length L Ch R = 1 ,4547    ,171.1,171.1,171.1
XS GIS Cut Line= 3
2186040.09359268303255.4649556632186284.85450341303338.251734292
2186689.78983367303356.248860082
#Sta/Elev= 30
       0 2196.48    26.1 2178.35    57.2 2154.99    81.5 2138.14   112.6  2114.4
   135.9 2095.25     140 2091.77   149.1 2082.01  154.562079.599   164.6 2077.47
  173.762079.601   199.2 2081.77   261.4  2080.6  314.572081.634   343.5 2081.66
   360.1 2080.72   384.1 2081.95  436.36  2081.9     446 2080.92   458.5 2083.55
   474.9 2085.82   497.9 2085.66     511 2083.64   527.4    2084   540.6  2087.7
  557.422094.231   569.7 2099.44   586.2 2103.13   622.7 2115.11   663.7 2127.38
#Mann= 6 ,-1 , 0
       0      .1       0  154.56    .045       0  173.76      .1       0
  314.57      .1       0  436.36     .06       0  557.42      .1       0
Bank Sta=154.56,173.76
XS Rating Curve= 0 ,0
Exp/Cntr(USF)=0,0
Exp/Cntr=0.3,0.1

Type RM Length L Ch R = 1 ,4375    ,241.8,241.8,241.8
XS GIS Cut Line= 4
2185950.10796374303385.0442613442186148.07634742303478.629315447
2186304.65134178303478.6293154472186718.58523493303390.443399081
#Sta/Elev= 30
       0 2237.71    28.9 2218.69    94.2 2172.04   130.5 2142.18  157.422118.856
   172.5 2105.61   192.2 2089.86     203 2083.26   210.3 2080.28   234.1 2078.89
   243.32076.644   253.8 2075.46  264.522076.643   273.5 2078.47     303 2079.14
   342.4 2078.25  427.272078.627   472.4 2078.16   519.4 2080.15  543.482078.603
   566.4  2079.3   583.1 2083.83   593.2 2085.11  671.612084.656   683.5 2085.71
   697.3 2089.31   720.7  2096.4   733.2 2101.97   771.9 2115.12   798.8 2121.68
#Mann= 7 ,-1 , 0
       0      .1       0  157.42      .1       0   243.3    .045       0
  264.52      .1       0  427.27      .1       0  543.48     .06       0
  671.61      .1       0
Bank Sta=243.3,264.52
XS Rating Curve= 0 ,0
Exp/Cntr(USF)=0,0
Exp/Cntr=0.3,0.1

Type RM Length L Ch R = 1 ,4134    ,247.4,247.4,247.4
XS GIS Cut Line= 4
 2185885.3183109303430.037075817 2186175.0720361303660.400285916
2186284.85450341 303753.985340022186504.41943804303910.560334384
#Sta/Elev= 30
       0 2216.34    49.2 2183.45    98.2 2147.04   111.9 2138.23   121.5 2130.03
  143.652114.166   175.8 2092.92   193.9 2083.59   204.1 2079.42   220.9 2076.37
  270.042075.295   304.92075.092   355.1 2075.22   375.9 2074.31   391.1 2075.01
  401.68 2074.12  422.132072.853   445.1 2071.36     4552072.854   469.1 2076.87
  501.892080.929   606.8 2090.82   626.2 2093.24     638 2096.19  652.412096.324
   664.8 2096.29   681.8 2099.89   731.7 2107.47   751.9 2113.86   784.1 2127.89
#Mann= 9 ,-1 , 0
       0      .1       0  143.65      .1       0  270.04     .06       0
   304.9      .1       0  401.68      .1       0  422.13    .045       0
     455      .1       0  501.89     .06       0  652.41      .1       0
Bank Sta=422.13,455
XS Rating Curve= 0 ,0
Exp/Cntr(USF)=0,0
Exp/Cntr=0.3,0.1

Type RM Length L Ch R = 1 ,3886    ,407.6,407.6,407.6
XS GIS Cut Line= 4
2185741.34130458303534.4204053932186016.69732916303856.568957017
2186108.48267068  303917.75918472186380.23927009304124.726131274
#Sta/Elev= 30
       0 2201.43   124.1 2120.03   169.6 2085.23  184.612075.246   187.9 2074.05
   194.8 2073.29  252.752072.517   295.8 2070.56  318.262070.751  367.332071.606
   414.5  2070.2   473.7 2071.31  479.982069.567   489.5 2067.91   501.3  2068.5
  506.392069.566   545.2 2070.61   565.8 2070.24   569.9  2072.1   577.1 2079.21
   586.4 2086.76   598.8 2095.86   602.9 2097.85   612.2 2098.64   626.3 2098.38
   635.9 2103.14  669.962109.473   722.3 2118.82   763.7 2127.32   875.7 2153.33
#Mann= 8 ,-1 , 0
       0      .1       0  184.61      .1       0  252.75     .05       0
  318.26     .06       0  367.33     .05       0  479.98    .045       0
  506.39     .06       0  669.96      .1       0
Bank Sta=479.98,506.39
XS Rating Curve= 0 ,0
Exp/Cntr(USF)=0,0
Exp/Cntr=0.3,0.1

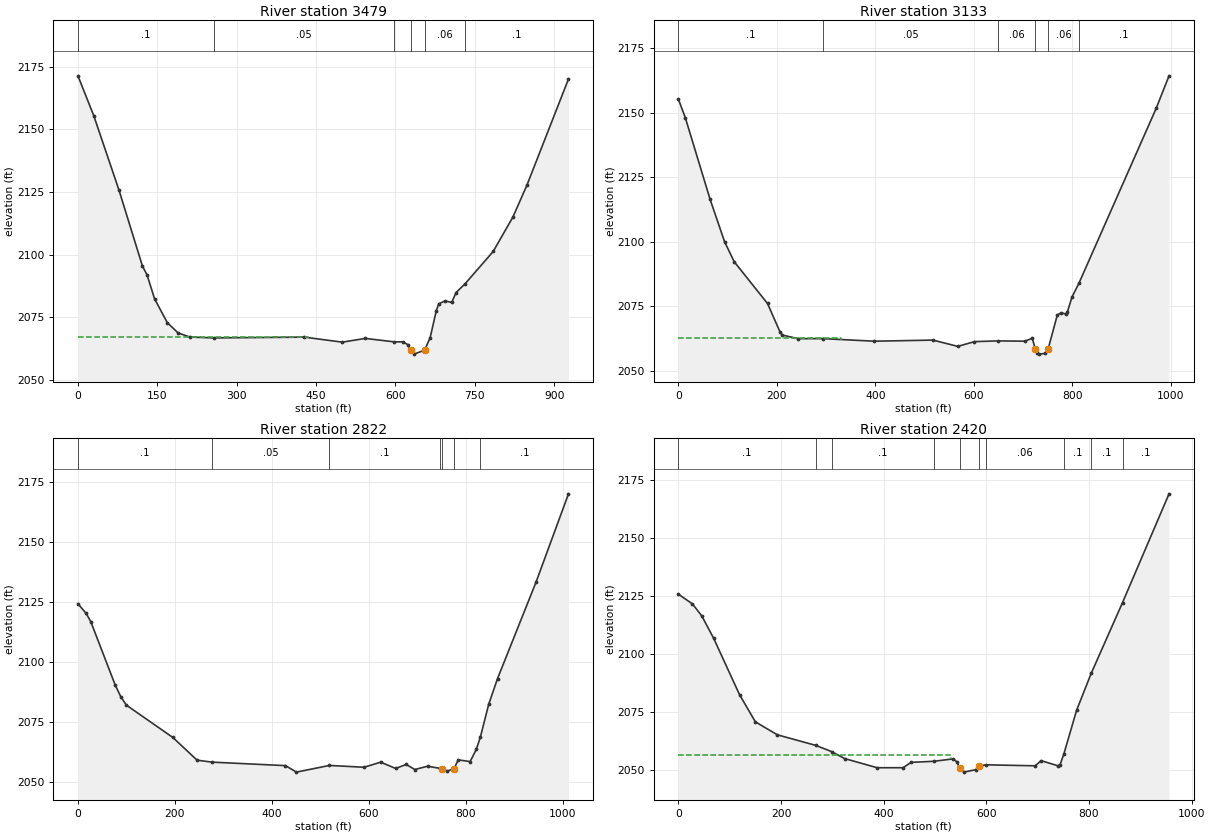
Type RM Length L Ch R = 1 ,3479    ,345.1,345.1,345.1
XS GIS Cut Line= 3
2185420.99246554303735.9882142312185775.53584358304113.927855801
2186029.29531721304434.276694846
#Sta/Elev= 30
       0 2171.32    29.9  2155.4    77.4  2125.8   121.9 2095.39   130.6 2091.85
   144.9 2082.26   168.9  2072.8   189.4 2068.68     212 2067.06  256.23 2066.72
   427.8 2067.03   499.5 2065.03   542.9 2066.52   598.12065.136   614.2 2065.15
   623.5 2064.01  628.982061.835     635 2060.25  655.112061.835   665.5 2066.83
   677.2 2077.65   681.8 2080.34   693.4 2081.47   706.2 2080.89   714.5 2084.84
  731.372088.296   784.6 2101.22     822 2115.01   848.5 2127.75   926.9 2170.06
#Mann= 6 ,-1 , 0
       0      .1       0  256.23     .05       0   598.1     .06       0
  628.98    .045       0  655.11     .06       0  731.37      .1       0
#XS Ineff= 2 , 0
          435.41 2067.05
Permanent Ineff=
       F       F
Bank Sta=628.98,655.11
XS Rating Curve= 0 ,0
Exp/Cntr(USF)=0,0
Exp/Cntr=0.3,0.1

Type RM Length L Ch R = 1 ,3133    ,311.1,311.1,311.1
XS GIS Cut Line= 3
2185118.64075228303860.1683821752185500.17981901304313.695952059
2185743.14101716304635.844503683
#Sta/Elev= 30
       0 2155.17    13.9 2148.06    64.3 2116.37    93.7 2099.95   113.2 2092.23
   180.8 2076.05   206.4 2064.94     211  2063.8   243.6 2062.41  293.782062.431
   397.3 2061.43   516.7 2061.86   567.3 2059.42   600.9 2061.26  648.012061.548
   703.7 2061.44   718.5 2062.59  724.26 2058.54   728.3 2056.81   732.4 2056.42
   744.8 2056.69   750.92058.539   769.4 2071.66   777.6 2072.44   787.3 2071.93
   789.7 2072.69   799.1 2078.56  813.142083.857   970.1  2151.7   996.2 2164.31
#Mann= 6 ,-1 , 0
       0      .1       0  293.78     .05       0  648.01     .06       0
  724.26    .045       0   750.9     .06       0  813.14      .1       0
#XS Ineff= 2 , 0
          329.62 2062.79
Permanent Ineff=
       F       F
Bank Sta=724.26,750.9
XS Rating Curve= 0 ,0
Exp/Cntr(USF)=0,0
Exp/Cntr=0.3,0.1

Type RM Length L Ch R = 1 ,2822    ,402.2,402.2,402.2
XS GIS Cut Line= 3
2184918.87265602303986.1482626982185233.82235733 304493.66720995
2185509.17838191304803.217773521
#Sta/Elev= 30
       0 2124.29      17 2120.26    26.5 2116.84    76.6  2090.6    88.2 2085.69
    99.8 2082.13   195.7 2068.67   245.7 2059.22  276.912058.403     428 2056.95
   450.6 2054.25  518.552057.031   590.2 2056.28   624.3 2058.39   655.1 2055.78
     677 2057.44   694.6 2055.34   720.9  2056.7  746.64 2055.82   751.7 2055.72
   761.6  2054.7  775.372055.643   784.2 2059.35   808.8 2058.64   821.4 2063.69
   829.72068.691     847 2082.43   865.2 2093.13   944.6 2133.25  1011.6 2170.02
#Mann= 7 ,-1 , 0
       0      .1       0  276.91     .05       0  518.55      .1       0
  746.64     .06       0   751.7    .045       0  775.37     .06       0
   829.7      .1       0
Bank Sta=751.7,775.37
XS Rating Curve= 0 ,0
Exp/Cntr(USF)=0,0
Exp/Cntr=0.3,0.1

Type RM Length L Ch R = 1 ,2420    ,512.3,512.3,512.3
XS GIS Cut Line= 4
2184708.30628429304140.923544484 2184963.8654705304544.059162159
2184949.46776987304693.4353062082185104.24305165304983.189031412
#Sta/Elev= 30
       0 2125.77    27.3 2121.58    45.5 2116.37    68.7 2106.67   119.1 2082.33
   149.8 2070.66   192.7 2065.05  267.572060.491  298.332057.807   323.6 2054.81
   387.2 2050.84   437.7 2050.85   453.2 2053.16  497.712053.625   535.2 2054.66
   542.6 2053.36   547.9 2050.66   555.8 2048.94   578.8 2049.96   585.4 2051.47
  598.372052.105   695.3 2051.67   706.5  2053.9     740 2051.64   743.7  2052.2
  750.982056.806   775.8 2075.66   804.2 2091.58  865.292122.168   955.9 2169.14
#Mann= 10 ,-1 , 0
       0      .1       0  267.57     .05       0  298.33      .1       0
  497.71      .1       0   547.9    .045       0   585.4      .1       0
  598.37     .06       0  750.98      .1       0   804.2      .1       0
  865.29      .1       0
#XS Ineff= 2 , 0
           531.2  2056.3
Permanent Ineff=
       F       F
Bank Sta=547.9,585.4
XS Rating Curve= 0 ,0
Exp/Cntr(USF)=0,0
Exp/Cntr=0.3,0.1