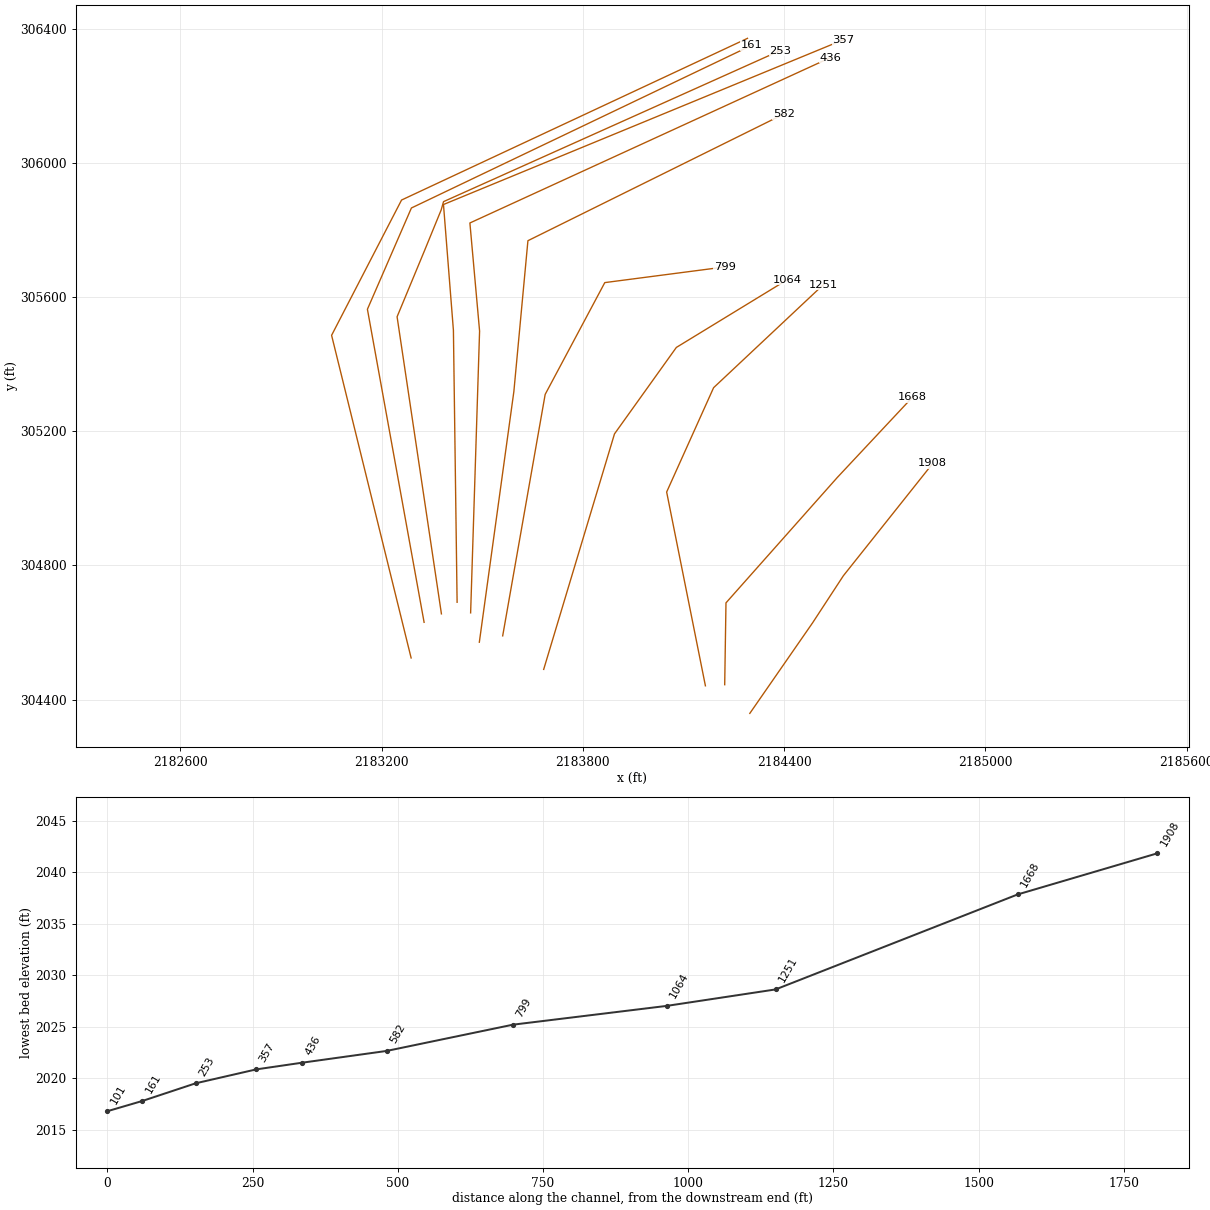
HEC-RAS study SLPHRLCKRN.prj: SLPHRLCKRN

--- SLPHRLCKRN.g01 (geometry) --- (continued)

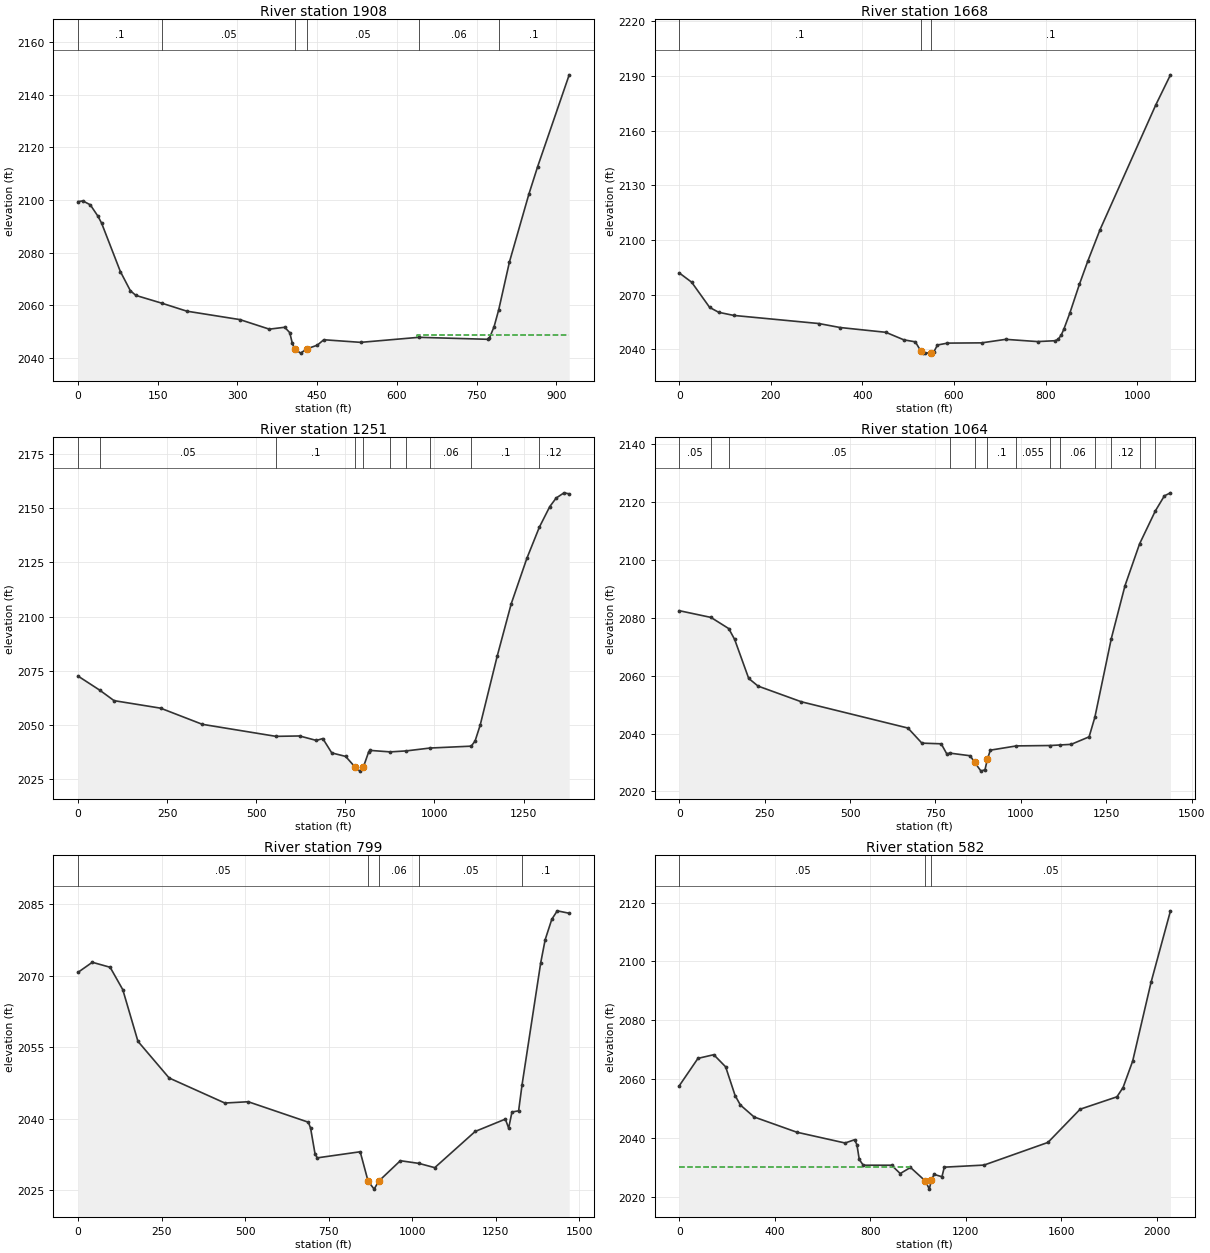
Type RM Length L Ch R = 1 ,1908    ,239.8,239.8,239.8
XS GIS Cut Line= 4
 2184297.9718163304358.6887665322184485.14192451304628.645653367
2184576.92726603304769.0232345222184843.28472771305103.769774198
#Sta/Elev= 30
       0 2099.35     9.2 2099.61    23.2 2098.12    37.6 2093.79    44.4 2091.19
    79.7 2072.81    98.6  2065.5     109 2063.73  158.362060.741   204.7 2057.75
   304.6 2054.55   359.9 2050.92   388.9 2051.64   398.4 2049.59   403.1  2045.6
  407.292043.497   418.7 2041.82  431.132043.498   450.1 2044.83   462.4  2046.9
   531.8 2045.91  641.042047.821   771.1 2047.07   773.9 2047.51   782.8 2051.92
  791.532058.371   811.6 2076.44   848.1 2102.14   864.5 2112.54     924 2147.48
#Mann= 6 ,-1 , 0
       0      .1       0  158.36     .05       0  407.29    .045       0
  431.13     .05       0  641.04     .06       0  791.53      .1       0
#XS Ineff= 2 , 0
                          637.24         2048.59
Permanent Ineff=
       F       F
Bank Sta=407.29,431.13
XS Rating Curve= 0 ,0
Exp/Cntr(USF)=0,0
Exp/Cntr=0.3,0.1

Type RM Length L Ch R = 1 ,1668    ,416.8,416.8,416.8
XS GIS Cut Line= 4
2184223.11313716304444.1615398332184226.92519813 304688.13344166
2184558.57450217305061.7154163322184783.48609917305301.875257192
#Sta/Elev= 30
       0 2081.89    27.1 2076.79    66.4 2062.95    86.1 2060.27   118.9 2058.55
   304.6  2054.1   351.1 2051.91     451 2049.28   490.5 2045.13   515.5 2044.04
     5272039.213   531.5 2038.08   536.5 2037.84   549.92038.166   556.2 2038.65
   563.8  2042.3   585.7 2043.34   660.3 2043.48   712.9 2045.41   782.4 2044.18
   820.8 2044.66   827.4  2045.4   834.3 2047.88     840 2051.13   852.9 2059.87
   873.6 2075.54     892 2088.35   918.9 2105.71  1040.3 2174.05  1072.6 2190.69
#Mann= 3 , 0 , 0
       0      .1       0     527    .045       0   549.9      .1       0
Bank Sta=527,549.9
XS Rating Curve= 0 ,0
Exp/Cntr(USF)=0,0
Exp/Cntr=0.3,0.1

Type RM Length L Ch R = 1 ,1251    ,187.7,187.7,187.7
XS GIS Cut Line= 4
2184165.59295772304440.8978596422184050.05585389305018.583378797
2184190.03349892305329.6448121882184516.64800398305636.262510816
#Sta/Elev= 30
       0 2072.53   60.732066.048   101.2 2061.17   231.7  2057.7   348.8 2050.24
  555.552044.678   621.8 2044.86   668.9 2042.79   686.9 2043.66     712 2037.04
     751 2035.41  776.952030.579   791.2 2028.62  800.852030.581   815.5 2037.44
     820 2038.19     8762037.505  920.892037.958  987.592039.283 1103.242040.154
  1114.1 2042.51  1128.5 2049.89  1176.4 2081.85  1215.6 2105.94  1259.3 2126.83
 1294.512141.298  1323.6 2150.75  1341.6 2154.73  1363.7 2157.14  1378.2 2156.67
#Mann= 10 ,-1 , 0
       0    .055       0   60.73     .05       0  555.55      .1       0
  776.95    .045       0  800.85      .1       0     876     .05       0
  920.89    .055       0  987.59     .06       0 1103.24      .1       0
 1294.51     .12       0
Bank Sta=776.95,800.85
XS Rating Curve= 0 ,0
Exp/Cntr(USF)=0,0
Exp/Cntr=0.3,0.1

Type RM Length L Ch R = 1 ,1064    ,264.3,264.3,264.3
XS GIS Cut Line= 4
2183683.44773596304489.7789420322183894.52513719305191.889034543
2184078.94012985305449.6256507822184409.99836967305651.815582486
#Sta/Elev= 30
       0 2082.51   92.822080.181  144.832076.317   162.2 2072.56   203.3 2059.09
   230.7 2056.43   357.5    2051   669.5 2041.92   710.3  2036.7   766.8 2036.47
   782.9 2033.05  792.262033.246   851.5 2032.34   864.5 2030.11   883.3 2027.02
     895  2027.5   902.1 2031.15   910.7 2034.27  987.112035.744 1085.812035.878
 1113.952036.062  1147.3 2036.28  1199.8 2038.88 1216.69 2045.67 1264.832072.887
  1304.9 2091.17 1347.572105.631  1393.82117.035  1420.2 2122.23    1438 2123.27
#Mann= 13 ,-1 , 0
       0     .05       0   92.82     .12       0  144.83     .05       0
  792.26      .1       0   864.5    .045       0   902.1      .1       0
  987.11    .055       0 1085.81      .1       0 1113.95     .06       0
 1216.69      .1       0 1264.83     .12       0 1347.57      .1       0
  1393.8     .12       0
Bank Sta=864.5,902.1
XS Rating Curve= 0 ,0
Exp/Cntr(USF)=0,0
Exp/Cntr=0.3,0.1

Type RM Length L Ch R = 1 ,799     ,217.6,217.6,217.6
XS GIS Cut Line= 4
2183561.24502999304589.7629741932183687.89147073305309.648005756
2183865.64086124 305642.928112962184223.36150964305689.587327969
#Sta/Elev= 30
       0 2070.74    42.9 2072.86    96.2 2071.81     134 2067.11   179.4 2056.25
   272.7 2048.55   439.3 2043.29   509.2 2043.56   689.1 2039.26   695.8 2038.02
   709.1 2032.62   715.8 2031.77   844.2 2033.05  867.892026.849     886  2025.2
  899.36 2026.85   964.3 2031.17 1020.152030.603  1067.2 2029.71  1188.2 2037.32
  1278.4 2039.91  1288.3 2038.02  1298.2  2041.4  1318.1 2041.65 1328.412047.128
  1384.2 2072.76  1397.5  2077.6  1417.3 2081.89  1433.7 2083.67  1469.4 2083.16
#Mann= 5 ,-1 , 0
       0     .05       0  867.89    .045       0  899.36     .06       0
 1020.15     .05       0 1328.41      .1       0
#XS Ineff= 2 , 0
                          982.11         2030.75
Permanent Ineff=
       F       F
Bank Sta=867.89,899.36
XS Rating Curve= 0 ,0
Exp/Cntr(USF)=0,0
Exp/Cntr=0.5,0.3

Type RM Length L Ch R = 1 ,582     ,146,146,146
XS GIS Cut Line= 4
2183491.61103542304570.849064223 2183594.5366815305318.013013567
2183636.46935213 305767.836207562184398.88154533306145.230243198
#Sta/Elev= 30
       0 2057.76    78.3 2067.07   144.5 2068.32   194.2  2064.2   233.9 2054.43
     256 2051.22   313.4 2047.16   492.2 2041.99   694.3 2038.32     734 2039.43
   743.9 2037.73   753.7 2032.72   770.4 2030.78     889 2030.77   925.2 2027.94
   968.1 2030.02    1031 2025.37  1047.1 2022.65  1055.1  2025.6  1066.9 2027.65
  1099.9 2026.86  1109.7 2030.11  1276.1 2030.82  1543.8 2038.52  1678.4  2049.8
  1832.5 2054.01  1858.2 2057.17  1898.4 2066.15  1975.3  2092.9  2056.7  2117.2
#Mann= 3 , 0 , 0
       0     .05       0    1031    .045       0  1055.1     .05       0
#XS Ineff= 2 , 0
          964.04 2030.05
Permanent Ineff=
       F       F
Bank Sta=1031,1055.1
XS Rating Curve= 0 ,0
Exp/Cntr(USF)=0,0
Exp/Cntr=0.3,0.1

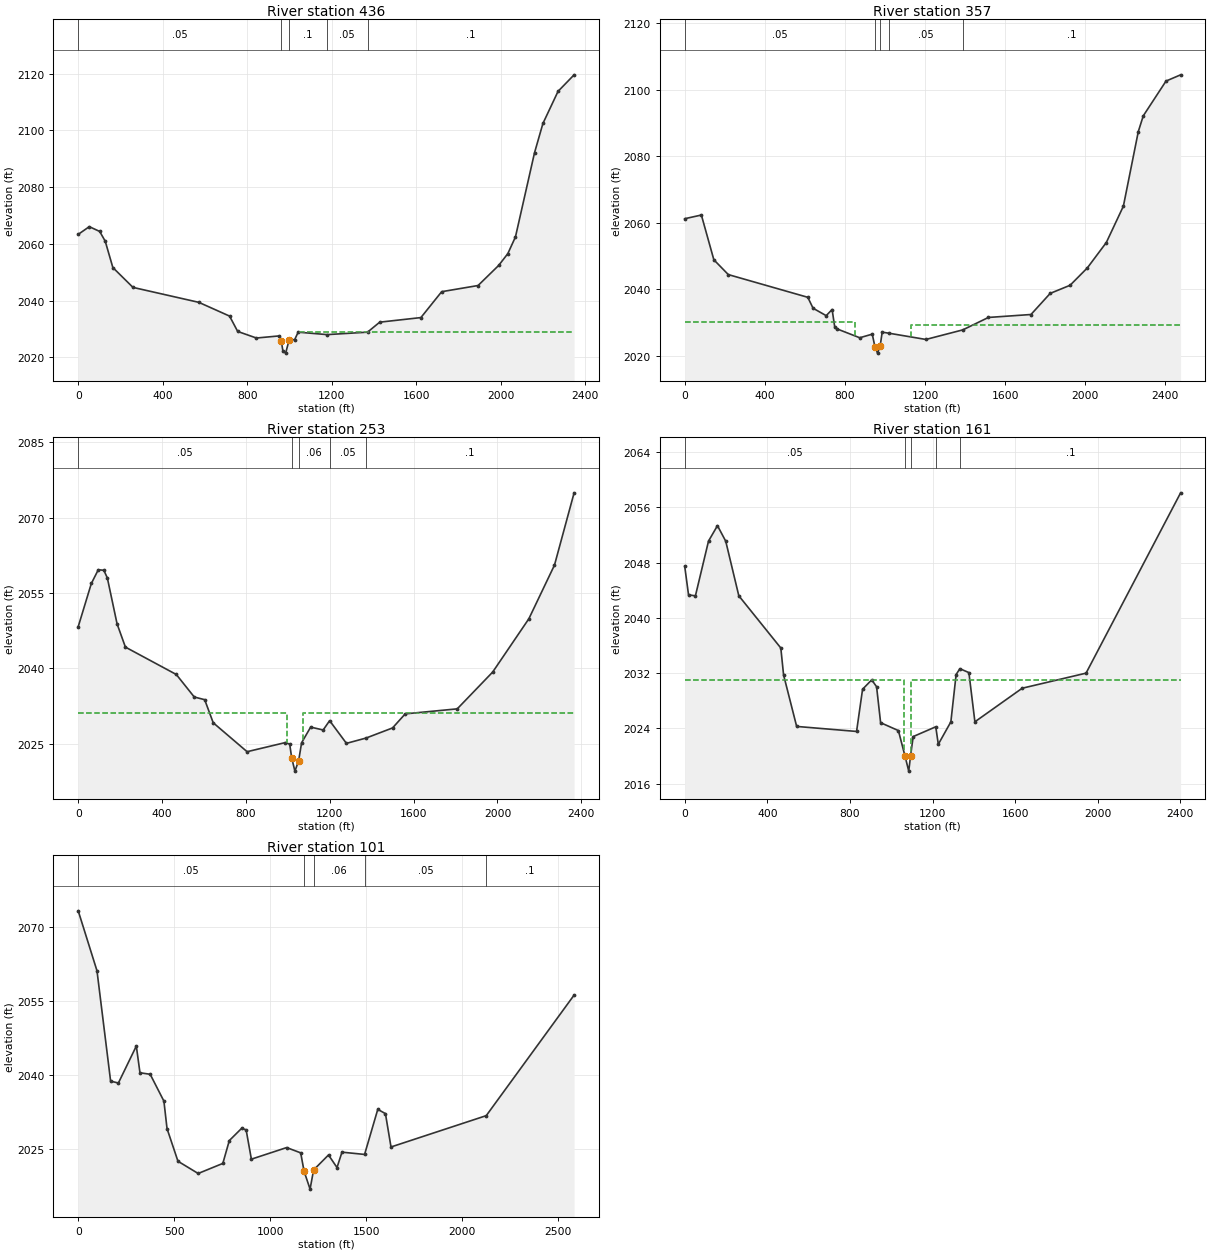
Type RM Length L Ch R = 1 ,436     ,78.4,78.4,78.4
XS GIS Cut Line= 4
2183465.65016497304658.3624302612183492.36714117305498.506733171
2183463.48286521305820.6775034692184538.86667779306313.932062132
#Sta/Elev= 30
       02063.344  52.388 2066.06 101.6252064.385 127.8852060.935 163.9932051.656
 259.1852044.665 571.0222039.395 716.3582034.553 754.8412029.144 843.4792026.827
  952.182027.576  960.88 2025.88  968.652022.358 981.8262021.505 998.2962026.125
1024.6482026.2731041.118 2028.891178.0252028.0281369.3282028.888 1427.082032.414
1621.993 2034.03 1720.282043.1511892.7042045.3291990.1612052.4062033.4752056.569
 2069.572062.4572159.8072092.1092199.5112102.4142271.1342113.7382347.1432119.558
#Mann= 5 ,-1 , 0
       0     .05       0  960.88    .045       0 998.296      .1       0
1178.025     .05       01369.328      .1       0
#XS Ineff= 2 , 0
                         1045.43         2029.02
Permanent Ineff=
       F       F
Bank Sta=960.88,998.296
XS Rating Curve= 0 ,0
Exp/Cntr(USF)=0,0
Exp/Cntr=0.5,0.3

Type RM Length L Ch R = 1 ,357     ,104.3,104.3,104.3
XS GIS Cut Line= 4
2183425.36661484304689.9374480042183414.35490867305500.481726399
2183384.73001025305875.7304396972184577.13217158306367.010005131
#Sta/Elev= 30
       0 2061.22   83.132062.328 145.4712048.891 217.6562044.444 614.6742037.621
 640.9232034.346 706.546 2032.11 736.076 2033.96   749.22028.695 762.3252028.095
 874.0752025.477 936.6042026.559 949.7692022.839 962.933 2020.86 976.0972022.971
 986.1752027.158 1018.882026.8511204.3542024.965 1388.872027.8421516.6122031.571
1729.3072032.4581825.3222038.7981924.6762041.2352010.7642046.4482105.6442054.078
2190.8052064.9842265.3222087.387 2290.162092.1122403.708 2102.552476.6782104.425
#Mann= 5 ,-1 , 0
       0     .05       0 949.769    .045       0 976.097     .06       0
 1018.88     .05       0 1388.87      .1       0
#XS Ineff= 2 , 0
          850.31  2030.3 1131.86         2029.42
Permanent Ineff=
       F       F
Bank Sta=949.769,976.097
XS Rating Curve= 0 ,0
Exp/Cntr(USF)=0,0
Exp/Cntr=0.5,0.3

Type RM Length L Ch R = 1 ,253     ,91.7,91.7,91.7
XS GIS Cut Line= 6
2183378.58606269304655.3451690822183246.41866381305541.057078394
2183326.90386075305735.1684357112183377.79891175305859.447048628
2183384.90054677305884.3027712112184388.32727889306334.550786321
#Sta/Elev= 30
       02048.263  62.6262056.862  95.7982059.604 122.335 2059.49 138.9212057.969
 185.361 2048.83 225.1672044.198 467.9672038.747 553.5662034.267 603.3232033.733
  644.042029.135  805.672023.375 987.5572025.1881008.8672024.8811018.4212022.143
1033.7282019.5091051.4872021.5651065.6932025.1561108.8112028.2721168.5792027.701
1199.3592029.5551279.5692025.0361373.0652026.0941499.4282028.1051560.0562030.911
1808.1782031.9061977.1892039.2342149.7962049.844 2272.062060.5292365.6142074.913
#Mann= 5 ,-1 , 0
       0     .05       01018.421    .045       01051.487     .06       0
1199.359     .05       01373.065      .1       0
#XS Ineff= 2 , 0
             995    2031 1074.52            2031
Permanent Ineff=
       F       F
Bank Sta=1018.421,1051.487
XS Rating Curve= 0 ,0
Exp/Cntr(USF)=0,0
Exp/Cntr=0.5,0.3

Type RM Length L Ch R = 1 ,161     ,60.3,60.3,60.3
XS GIS Cut Line= 4
2183326.93416589304630.1986071992183157.95709473305563.475387664
2183289.11226086 305865.379732332184302.69811128306349.872310895
#Sta/Elev= 30
       02047.441  18.4852043.312  51.827 2043.18 115.1762051.101  158.522053.339
 198.5312051.087  261.882043.183 465.2652035.622 478.6012031.726 541.9512024.268
 832.0242023.541 861.1612029.658 905.3762031.011 928.9142030.017 948.4512024.809
1034.5892023.6651066.7822019.9491084.6682017.7961093.2912019.956 1106.132022.798
1215.4832024.215 1227.752021.6831288.613 2024.931314.0682031.786 1332.252032.625
1375.8862032.0631404.9772024.9381634.069  2029.81943.1612031.9822401.041 2058.09
#Mann= 5 ,-1 , 0
       0     .05       01066.782    .045       01093.291     .06       0
1215.483     .05       0 1332.25      .1       0
#XS Ineff= 2 , 0
            1060    2031    1096            2031
Permanent Ineff=
       F       F
Bank Sta=1066.782,1093.291
XS Rating Curve= 0 ,0
Exp/Cntr(USF)=0,0
Exp/Cntr=0.5,0.3

Type RM Length L Ch R = 1 ,101     ,60.3,60.3,60.3
XS GIS Cut Line= 4
2183288.25929584304523.8915499442183051.16314854305485.806436384
2183259.73558029305889.0774274622184291.02143845306371.153972106
#Sta/Elev= 30
       0 2073.19    97.8 2061.04   168.8 2038.68   209.3  2038.3   302.7 2045.79
   321.7 2040.38   374.9 2040.07   446.4 2034.63   462.7 2029.06   519.6 2022.45
   624.9 2019.97   753.3 2022.01   787.1 2026.64   851.3 2029.12   874.7 2028.81
     902 2022.87  1085.8 2025.22  1158.9 2024.15  1176.5 2020.43  1207.7  2016.8
  1226.2 2020.69  1303.8 2023.72  1348.1 2021.17  1373.9 2024.29  1491.7 2023.83
  1560.5 2032.97  1600.4 2032.09  1629.3 2025.34  2125.5 2031.69  2583.1 2056.12
#Mann= 5 ,-1 , 0
       0     .05       0  1176.5    .045       0  1226.2     .06       0
  1491.7     .05       0  2125.5      .1       0
Bank Sta=1176.5,1226.2
XS Rating Curve= 0 ,0
Exp/Cntr(USF)=0,0
Exp/Cntr=0.5,0.3
Stream Node=ANGLINSCK       ,Main            , 0 , 0 ,Upstream end
Stream Node=ANGLINSCK       ,Main            , 0 , 1 ,Downstream end
Stream Node=GRBRRVTR1       ,Main            , 0 , 0 ,Upstream end
Stream Node=GRBRRVTR1       ,Main            , 0 , 1 ,Downstream end
Stream Node=GRBRRVTR2       ,Main            , 0 , 0 ,Upstream end
Stream Node=GRBRRVTR2       ,Main            , 0 , 1 ,Downstream end
Stream Node=GRBRRVTR4       ,Main            , 0 , 0 ,Upstream end
Stream Node=GRBRRVTR4       ,Main            , 0 , 1 ,Downstream end
Stream Node=HOMINYCK        ,Main            , 0 , 0 ,Upstream end
Stream Node=HOMINYCK        ,Main            , 0 , 1 ,Downstream end
Stream Node=HOWARDCK        ,Main            , 0 , 0 ,Upstream end
Stream Node=HOWARDCK        ,Main            , 0 , 1 ,Downstream end
Stream Node=JERCHODFT       ,Main            , 0 , 0 ,Upstream end
Stream Node=JERCHODFT       ,Main            , 0 , 1 ,Downstream end
Stream Node=JERCHODFTT1     ,Main            , 0 , 0 ,Upstream end
Stream Node=JERCHODFTT1     ,Main            , 0 , 1 ,Downstream end
Stream Node=LITTLECK2       ,Main            , 0 , 0 ,Upstream end
Stream Node=LITTLECK2       ,Main            , 0 , 1 ,Downstream end
Stream Node=SLPHRLCKRN      ,Main            , 0 , 0 ,Upstream end
Stream Node=SLPHRLCKRN      ,Main            , 0 , 1 ,Downstream end
Stream Node=SLSHLCKRN       ,Main            , 0 , 0 ,Upstream end
Stream Node=SLSHLCKRN       ,Main            , 0 , 1 ,Downstream end
Stream Node=YOUNGSCK        ,Main            , 0 , 0 ,Upstream end
Stream Node=YOUNGSCK        ,Main            , 0 , 1 ,Downstream end
LCMann Table=0

Chan Stop Cuts=-1
Use User Specified Reach Order=0
Composite Channel Slope=5